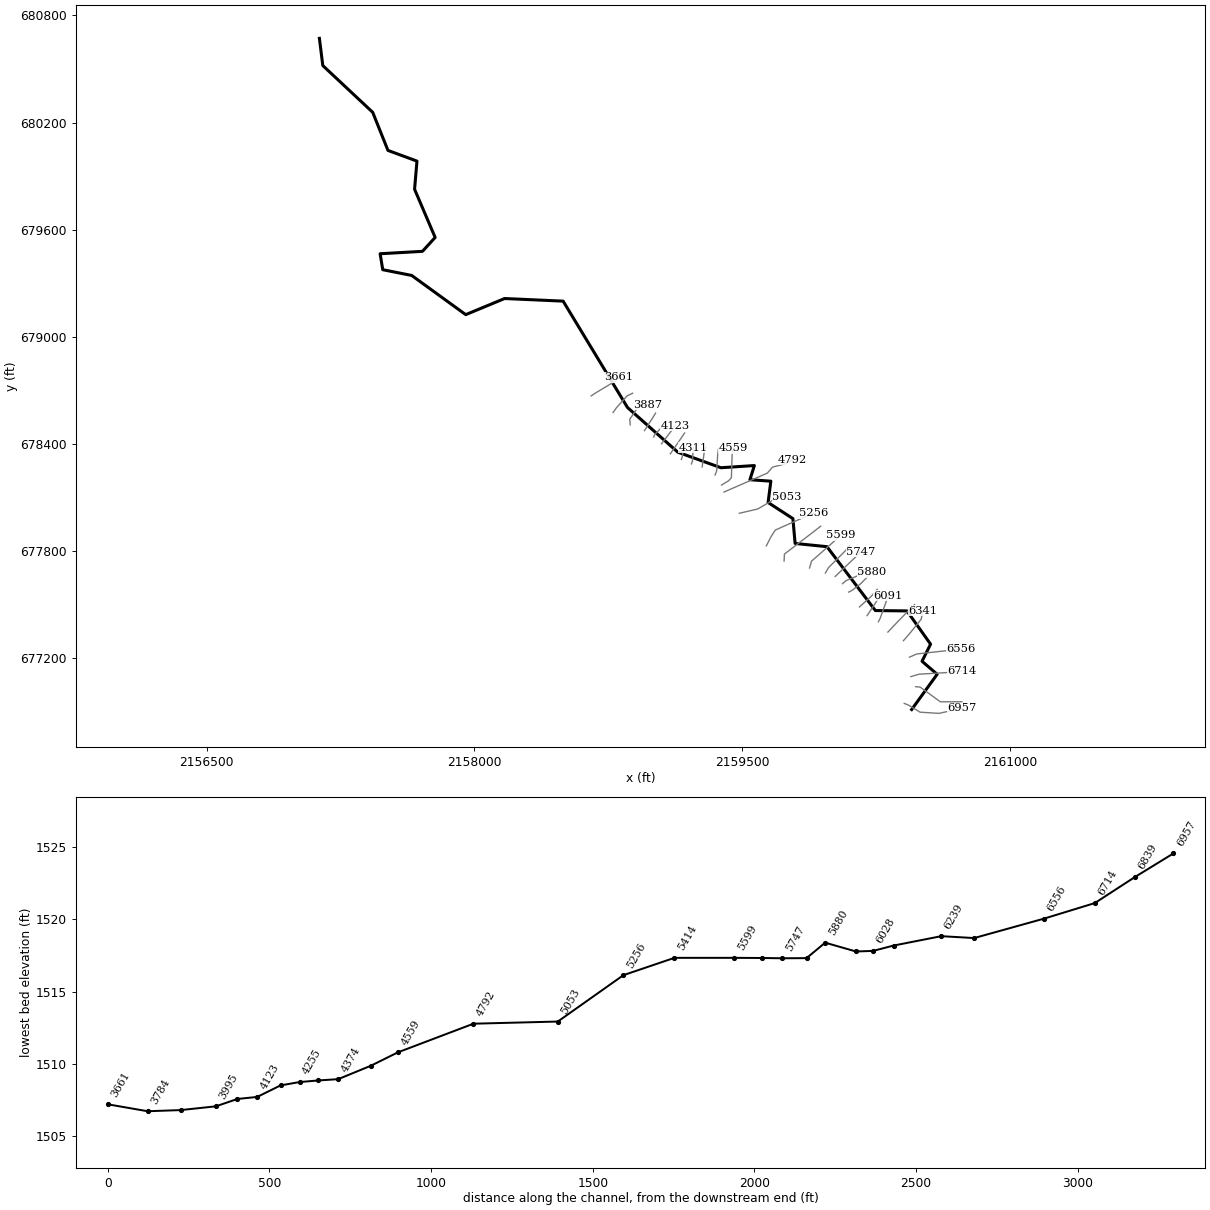
--- LFFRENCHCK.prj (project) ---

Proj Title=LFFRENCHCK
Current Plan=p01
Default Exp/Contr=0,0
English Units
Geom File=g01
Flow File=f01
Plan File=p01
BEGIN DESCRIPTION:
---------- MODELED AS PART OF WVEMD CTP PROGRAM, 2023----------
Stream Name: Left Fork French Creek
Flood Zone:  AFH
Upshur County, WV
HEC-RAS Version: RAS 6.3
Vertical Datum: NAVD88
Projection: NAD 1983 StatePlane West Virginia S FIPS 4702 (US Feet)
Terrain: 1-meter LIDAR (FEMA Region III 3DEP collected 2016-2018)
Land Use: 2019 NLCD
Hydrologic Method:
WV SIR2010-5033 regression equations
Additional Model Notes:
KWSE tie-in with French Creek
END DESCRIPTION:
DSS File=dss
DSS Export Rating Curves= 0
DSS Export Rating Curve Sorted= 0
DSS Export Volume Flow Curves= 0
DXF OffsetX= 0
DXF OffsetY= 0
DXF ScaleX= 0
DXF ScaleY= 0

--- LFFRENCHCK.p01 (plan) ---

Plan Title=Floodplain
Program Version=6.30
Short Identifier=Floodplain
Geom File=g01
Flow File=f01
Subcritical Flow
K Sum by GR= 0
Std Step Tol= 0.01
Critical Tol= 0.01
Num of Std Step Trials= 20
Max Error Tol= 0.3
Flow Tol Ratio= 0.001
Split Flow NTrial= 30
Split Flow Tol= 0.02
Split Flow Ratio= 0.02
Log Output Level= 0
Friction Slope Method= 1
Unsteady Friction Slope Method= 2
Unsteady Bridges Friction Slope Method= 1
Parabolic Critical Depth
Global Vel Dist= 0 , 0 , 0
Global Log Level= 0
CheckData=False
Encroach Param=-1 ,0,0, 0
Computation Interval=0.1SEC
Output Interval=1SEC
Instantaneous Interval=Max Profile
Mapping Interval=1HOUR
Computation Time Step Use Courant=        0
Computation Time Step Use Time Series=    0
Computation Time Step Count To Double=0
Computation Time Step Max Doubling=0
Computation Time Step Max Halving=0
Computation Time Step Residence Courant=0
Run HTab= 0
Run UNet= 0
Run Sediment= 0
Run PostProcess= 0
Run WQNet= 0
Run RASMapper=-1
UNET Theta= 0
UNET Theta Warmup= 0
UNET ZTol= 0
UNET ZSATol= 0
UNET MxIter= 0
UNET Max Iter WO Improvement= 0
UNET MaxInSteps= 0
UNET DtIC= 0
UNET DtMin= 0
UNET MaxCRTS= 0
UNET WFStab= 0
UNET SFStab= 0
UNET WFX= 1
UNET SFX= 1
UNET Gravity=32.17405
UNET 1D Methodology=Finite Difference
UNET DSS MLevel= 1
UNET Pardiso=0
UNET DZMax Abort= 0
UNET Use Existing IB Tables= 0
UNET Froude Reduction=False
UNET Froude Limit= 0
UNET Froude Power= 0
UNET D1 Cores= 0
UNET WindReference=Eulerian
UNET WindDragFormulation=Hsu (1988)
UNET D2 Coriolis=0
UNET D2 Cores= 0
UNET D2 Theta= 1
UNET D2 Theta Warmup= 1
UNET D2 Z Tol= 0.01
UNET D2 Volume Tol= 0.01
UNET D2 Max Iterations= 20
UNET D2 Equation= 0
UNET D2 RampUpFraction=0.1
UNET D2 TimeSlices= 1
UNET D2 Turbulence Formulation=Non-Conservative (original)
UNET D2 Eddy Viscosity=0.3
UNET D2 Transverse Eddy Viscosity=0.1
UNET D2 Smagorinsky Mixing=0
UNET D2 BCVolumeCheck=0
UNET D2 Cores=0
UNET D2 SolverType=PARDISO (Direct)
UNET D2 Minimum Iterations= 3
UNET D2 Maximum Iterations= 30
UNET D2 Restart Number= 10
UNET D2 Relaxation Coeff=1.3
UNET D2 SOR Precondition Iterations= 10
UNET D2 ILUT Maximum Fill= 8
UNET D2 ILUT Tolerance=1E-08
UNET D2 Convergence Tolerance=0.00001
UNET D1D2 MaxIter= 0
UNET D1D2 ZTol=0.01
UNET D1D2 QTol=0.1
UNET D1D2 MinQTol=1
DSS File=dss
Write IC File= 0
Write IC File at Fixed DateTime=0
Write IC File at Sim End=0
Echo Input=False
Echo Parameters=False
Echo Output=False
Write Detailed= 0
HDF Write Warmup=0
HDF Write Time Slices=0
HDF Flush=0
HDF Compression= 1
HDF Chunk Size= 1
HDF Spatial Parts= 1
HDF Use Max Rows=0
HDF Fixed Rows= 1
Calibration Method= 0
Calibration Iterations= 20
Calibration Max Change=0.05
Calibration Tolerance=0.2
Calibration Maximum=1.5
Calibration Minimum=0.5
Calibration Optimization Method= 1
WQ AD Non Conservative
WQ ULTIMATE=-1
WQ Max Comp Step=1HOUR
WQ Output Interval=15MIN
WQ Output Selected Increments= 0
WQ Output face flow=0
WQ Output face velocity=0
WQ Output face area=0
WQ Output face dispersion=0
WQ Output cell volume=0
WQ Output cell surface area=0
WQ Output cell continuity=0
WQ Output cumulative cell continuity=0
WQ Output face conc=0
WQ Output face dconc_dx=0
WQ Output face courant=0
WQ Output face peclet=0
WQ Output face adv mass=0
WQ Output face disp mass=0
WQ Output cell mass=0
WQ Output cell source sink temp=0
WQ Output nsm pathways=0
WQ Output nsm derived pathways=0
WQ Create Restart=0
WQ Fixed Restart=0
WQ System Summary=0
WQ Write To DSS=0
Sorting and Armoring Iterations= 10
XS Update Threshold= 0.02
Bed Roughness Predictor= 0
Hydraulics Update Threshold= 0.02
Energy Slope Method= 1
Volume Change Method= 1
Sediment Retention Method= 0
Sediment TS Multiplier= 1
Warm Up Method= 0
XS Weighting Method= 0
Number of US Weighted Cross Sections= 1
Number of DS Weighted Cross Sections= 1
Upstream XS Weight=0
Main XS Weight=1
Downstream XS Weight=0
Number of DS XS's Weighted with US Boundary= 1
Upstream Boundary Weight= 1
Weight of XSs Associated with US Boundary= 0
Number of US XS's Weighted with DS Boundary= 1
Downstream Boundary Weight= 0.5
Weight of XSs Associated with DS Boundary= 0.5
Percentile Method= 0
Sediment Output Level= 3
Mass or Volume Output= 0
Output Increment Type= 1
Profile and TS Output Increment= 1
Transport Output Increment 1
XS Output Flag= 0
XS Output Increment= 10
Read HDF5 Sediment Hotstart= 0
Sediment Hotstart Type= 0
Write Gradation File= 0
Read Gradation Hotstart= 0
Write HDF5 File= 1
Write Binary Output= 1
Write DSS Sediment File= 0
DSS Sediment Output Type= 1
SV Curve= 0
Specific Gage Flag= 0
Subcell Erosion Methods= 0
Subcell Deposition Methods= 0
Advection Scheme= 1
Matrix Solver= 0
Implicit Weighting Factor= 1
Maximum Outer Loop Convergence Iterations= 5
Convergence Maximum Absolute= 0.001
Convergence RMSE= 0.0001
Grain Fractions Max Abs Error= 0.001
Max Subgrid Regions= 1
Max Subgrid Length Scale= 3.402823E+38
Initial Layer Thickness= 3.402823E+38
Min Layer Thickness= 3.402823E+38
Max Layer Thickness= 3.402823E+38
Number of Layers= 5

--- LFFRENCHCK.f01 (steady flow) ---

Flow Title=Flows
Program Version=6.31
Number of Profiles= 1
Profile Names=01pct
River Rch & RM=LFFRENCHCK,Main,6957
     339
River Rch & RM=LFFRENCHCK,Main,4792
     395
River Rch & RM=LFFRENCHCK,Main,1979
     645
Boundary for River Rch & Prof#=LFFRENCHCK,Main            , 1
Up Type= 0
Dn Type= 1
Dn Known WS=1483.3
DSS Import GetInterval= 0
DSS Import GetPeak= 0
DSS Import FillOption= 0

--- LFFRENCHCK.g01 (geometry) ---

Geom Title=Geometry
Program Version=6.31

River Reach=LFFRENCHCK      ,Main
Reach XY= 30
2160449.65413076 676911.45971857     2160592.566677109.088000014
2160507.83200005677181.9450000082160555.59300001677277.810000017
2160423.50000003677463.9890000082160246.30700003677466.077999994
2159975.11000004677823.897000015     2159796.772677841.953999996
2159784.41595422677981.1299752592159645.42000003 678071.31400001
2159660.84499998678190.788000017     2159543.575678198.915000021
2159568.58499999678278.2960000192159381.34800003678266.106000006
2159139.59700003678353.2710000132158857.72599998678603.693000004
2158497.33100004679199.3439999972158169.41600002679214.024000019
2157951.61600001679123.7100000082157648.79800002679343.313000008
2157486.74300003679375.4770000132157472.12000003      679464.875
     2157709.264679478.3250000182157780.37599999679556.133000016
2157665.08000004679826.0999999942157678.44400002679983.746999994
2157515.96000004680043.726999998     2157430.483680257.206000015
2157151.01600003680518.9309999942157131.89861514680671.559536323

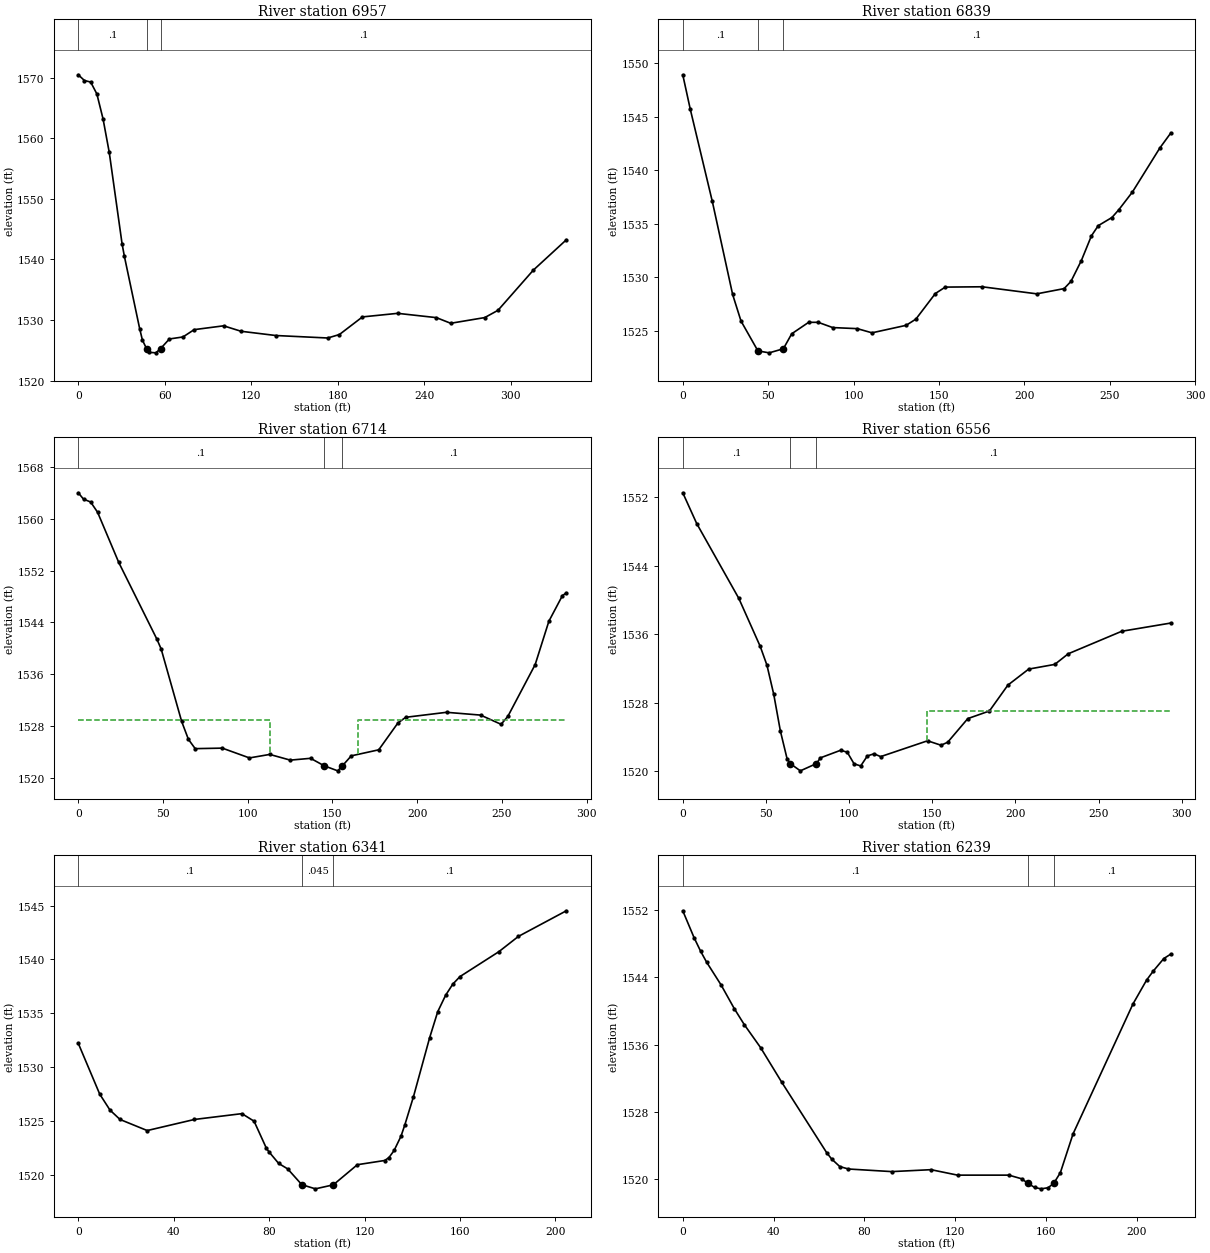
Type RM Length L Ch R = 1 ,6957    ,119,118.1,117.2
XS GIS Cut Line= 5
2160408.20533128  676945.75517082160433.16312274676935.888136966
2160496.84852164676896.7857168872160602.30166024676890.047235158
2160730.54108824676918.266356106
#Sta/Elev= 30
       0 1570.47     4.3 1569.52     8.6 1569.27    12.9 1567.31    17.2 1563.18
    21.5 1557.65    30.4 1542.55      32 1540.49    42.6 1528.55    44.5 1526.67
47.399221525.241    49.1 1524.66    53.8 1524.5757.098851525.268    63.2 1526.86
    72.6 1527.19    80.4  1528.4   100.8 1529.03   112.9 1528.13     137 1527.43
     173 1527.02   181.1 1527.59   197.1  1530.5   221.5 1531.09   248.4 1530.38
   258.3 1529.45   281.9 1530.39   291.1 1531.59   315.6 1538.22   338.5 1543.23
#Mann= 3 ,-1,0
       0      .1       047.39922    .045       057.09885      .1       0
Bank Sta=47.39922,57.09885
XS Rating Curve= 0 ,0
Exp/Cntr(USF)=0,0
Exp/Cntr=0.3,0.1

Type RM Length L Ch R = 1 ,6839    ,119.4,125.3,133
XS GIS Cut Line= 4
2160471.77662489677039.5437192142160497.31483011677037.222064194
2160610.49551231676954.8033109972160730.64115958676955.383724752
#Sta/Elev= 30
       0 1548.92     4.4  1545.7    17.3 1537.09    29.2  1528.4    34.1 1525.92
      44 1523.13    50.6 1522.95    58.9 1523.33    63.8 1524.73    73.7  1525.8
    79.3  1525.8    87.8 1525.31   102.2 1525.21   110.8 1524.82   130.8 1525.52
   136.5  1526.1   147.9 1528.49   153.7 1529.09   175.3 1529.12   207.3 1528.46
   223.3 1528.95   227.3 1529.62   233.4 1531.57   239.3 1533.88   243.3 1534.83
   251.3 1535.59   255.3 1536.31   263.3 1537.97   279.3 1542.07   285.8 1543.49
#Mann= 3 ,-1,0
       0      .1       0      44    .045       0    58.9      .1       0
Bank Sta=44,58.9
XS Rating Curve= 0 ,0
Exp/Cntr(USF)=0,0
Exp/Cntr=0.3,0.1

Type RM Length L Ch R = 1 ,6714    ,159.4,157.6,157.7
XS GIS Cut Line= 4
2160445.22115117677095.9775469382160491.08100341677109.592190572
2160652.30704644677118.9074730582160730.41210728677128.222755544
#Sta/Elev= 30
       0 1563.98     3.1    1563     7.3 1562.56    11.4 1560.98    23.9 1553.24
    46.4 1541.42    48.9 1539.92      61 1528.75      65 1525.98      69 1524.55
      85 1524.63     101 1523.12     113 1523.66   125.1 1522.78   137.1 1523.06
   145.1 1521.91   153.1 1521.13   155.7 1521.86   161.1 1523.44   177.3 1524.37
   188.6  1528.5   193.2 1529.38   217.3 1530.15   237.4 1529.72   249.5  1528.3
   253.5 1529.53   269.6  1537.5   277.7 1544.19   285.7 1548.14     288 1548.55
#Mann= 3 ,-1,0
       0      .1       0   145.1    .045       0   155.7      .1       0
#XS Ineff= 2 , 0
          113.05 1528.98  164.96         1528.92
Permanent Ineff=
       F       F
Bank Sta=145.1,155.7
XS Rating Curve= 0 ,0
Exp/Cntr(USF)=0,0
Exp/Cntr=0.3,0.1

Type RM Length L Ch R = 1 ,6556    ,203.1,215.3,221.7
XS GIS Cut Line= 4
2160437.33898906677204.8946960072160478.18291996677222.808700789
2160634.39304166677240.0061453782160725.39618594677251.471108438
#Sta/Elev= 30
       0 1552.52     8.4 1548.92    33.7 1540.19    46.6 1534.57    50.6  1532.4
    54.7 1528.99    58.7  1524.7    62.7 1521.48    64.61520.901    70.7 1520.05
    80.31520.889    82.8 1521.57    94.9 1522.45    98.9 1522.23     103 1520.87
     107 1520.62     111 1521.79     115 1522.04     119 1521.71   147.2 1523.56
   155.3 1523.04   159.3 1523.39   171.4 1526.15   184.4 1527.04   195.5 1530.06
     208 1531.93   223.7 1532.48   231.8 1533.72     264 1536.35   293.5 1537.31
#Mann= 3 ,-1,0
       0      .1       0    64.6    .045       0    80.3      .1       0
#XS Ineff= 2 , 0
                          147.04         1527.04
Permanent Ineff=
       F       F
Bank Sta=64.6,80.3
XS Rating Curve= 0 ,0
Exp/Cntr(USF)=0,0
Exp/Cntr=0.3,0.1

Type RM Length L Ch R = 1 ,6341    ,102.6,101.7,99.8
XS GIS Cut Line= 4
2160403.47880025677297.1265891492160441.52814641677340.980072853
2160502.79404276677417.0787651642160513.11250951677464.801673901
#Sta/Elev= 30
       0 1532.22       9  1527.5    13.3 1526.02    17.5 1525.15    28.9 1524.12
    48.7 1525.15    68.6 1525.69    73.7 1524.99    78.9 1522.46      80 1522.13
      84 1521.07    87.8 1520.56    93.71519.098    99.4 1518.71   106.9 1519.08
     117 1520.95   128.4 1521.34   130.2  1521.6   132.4 1522.27   135.3  1523.6
   136.9 1524.65   140.5 1527.25   147.3 1532.74   150.7 1535.16     154 1536.68
     157 1537.71     160 1538.41   176.3 1540.72   184.5 1542.14   204.6 1544.52
#Mann= 3 ,-1,0
       0      .1       0    93.7    .045       0   106.9      .1       0
Bank Sta=93.7,106.9
XS Rating Curve= 0 ,0
Exp/Cntr(USF)=0,0
Exp/Cntr=0.3,0.1

Type RM Length L Ch R = 1 ,6239    ,143.4,147.7,150.2
XS GIS Cut Line= 5
2160316.58487571677345.5329978622160363.07601748677394.636001527
 2160436.2081506677469.8576241632160458.94055905677488.663128269
2160465.80280306 677499.78117775
#Sta/Elev= 30
       0 1551.92       5 1548.71     7.9 1547.09    10.5 1545.81    16.9 1543.09
    22.7 1540.28    27.1 1538.38    34.3 1535.64    43.6 1531.53    63.4 1523.15
    65.6 1522.39    69.2 1521.49      73  1521.2    92.1 1520.89   109.4 1521.12
   121.1 1520.47   143.7 1520.47   149.3 1520.04   152.2 1519.48   155.1    1519
   157.9 1518.84     161 1518.97   163.5  1519.5   166.4 1520.76     172 1525.38
   198.4 1540.83   204.4 1543.67   207.3 1544.73     212 1546.24   215.1 1546.77
#Mann= 3 ,-1,0
       0      .1       0   152.2    .045       0   163.5      .1       0
Bank Sta=152.2,163.5
XS Rating Curve= 0 ,0
Exp/Cntr(USF)=0,0
Exp/Cntr=0.3,0.1

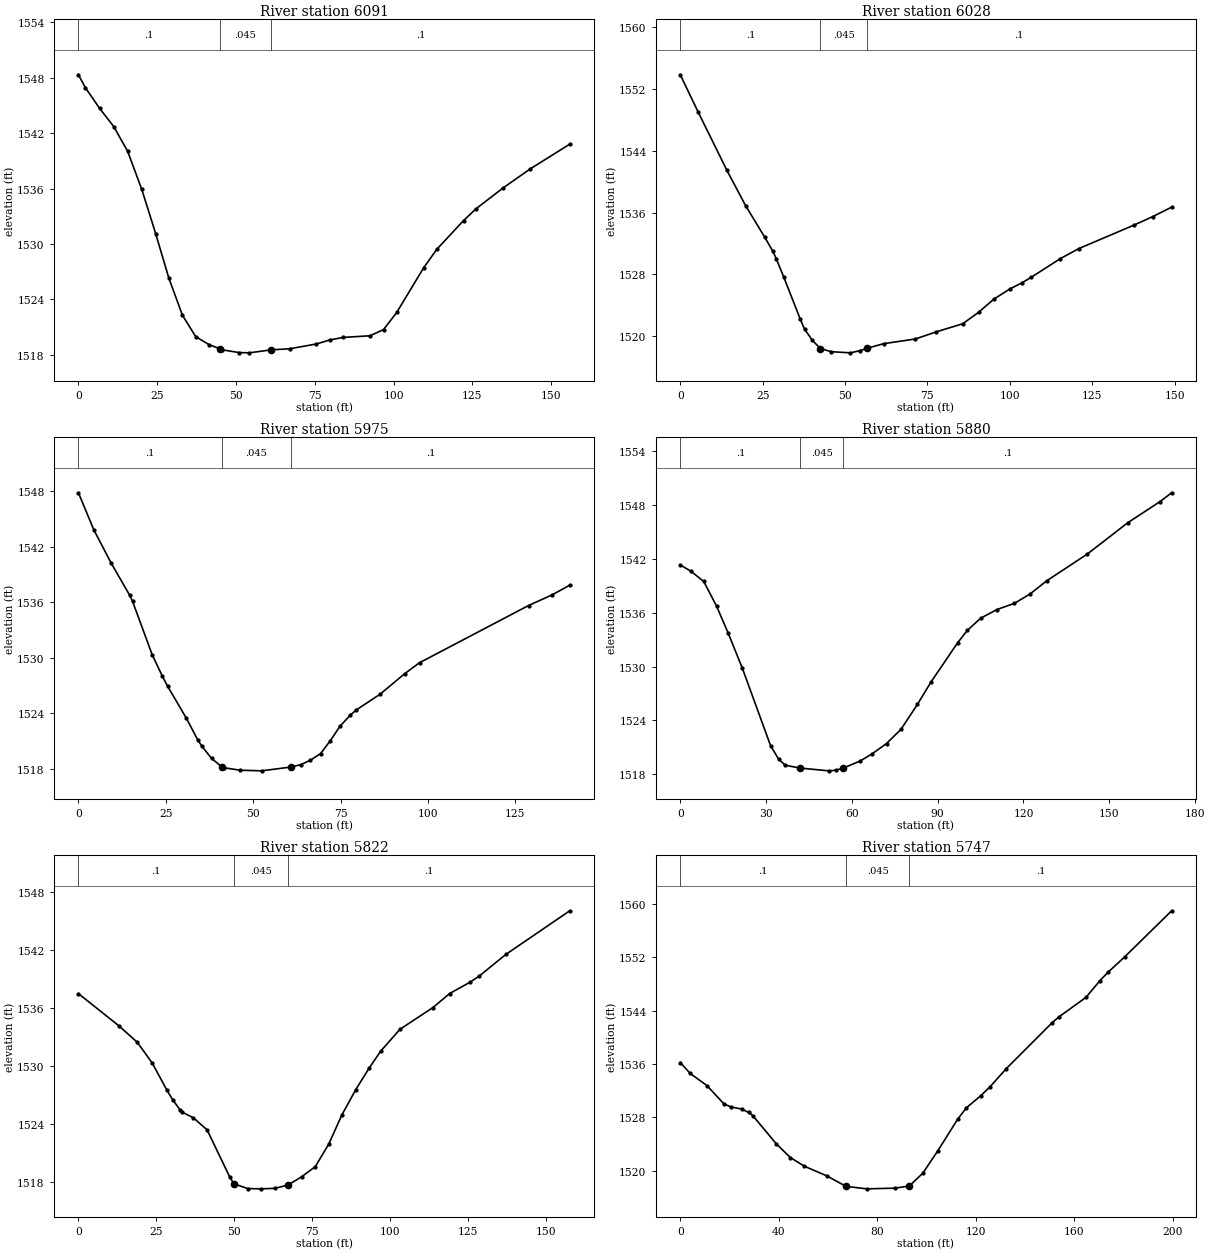
Type RM Length L Ch R = 1 ,6091    ,66.2,63.2,60.2
XS GIS Cut Line= 5
2160263.38815006677403.2372772042160273.28919614677422.658559898
2160303.75395331677507.198261039 2160311.3701426677530.046828914
2160318.98633189 677548.70649268
#Sta/Elev= 30
       0 1548.33     2.2 1546.94     6.7  1544.7    11.2 1542.72    15.6 1540.05
    20.1 1535.91    24.5 1531.12    28.7 1526.28      33 1522.27    37.2 1519.95
    41.5 1519.07    44.8 1518.65    45.7 1518.51      51 1518.22    54.2 1518.19
    61.21518.516      67 1518.63    75.5 1519.15    79.8 1519.59      84 1519.86
    92.5 1520.04    96.8 1520.71     101 1522.57   109.5 1527.39   113.7 1529.41
   122.2 1532.53   126.2 1533.82   134.8 1536.08   143.4 1538.14   155.9 1540.81
#Mann= 3 ,-1,0
       0      .1       0    44.8    .045       0    61.2      .1       0
Bank Sta=44.8,61.2
XS Rating Curve= 0 ,0
Exp/Cntr(USF)=0,0
Exp/Cntr=0.3,0.1

Type RM Length L Ch R = 1 ,6028    ,55.4,53,49.9
XS GIS Cut Line= 3
2160200.11810186677437.7360768352160260.30915793677528.739221123
2160288.25500539677557.401628773
#Sta/Elev= 30
       0 1553.87     5.4 1549.06    14.1 1541.52    19.8 1536.92    25.6 1532.83
    28.1 1530.98    29.1 1530.04    31.4 1527.64    36.4 1522.19    37.7 1520.89
    40.1 1519.43    42.5 1518.38    45.8 1517.97    51.6 1517.82    54.5  1518.1
    56.61518.397    61.7 1519.01    71.3 1519.61    77.6 1520.53    85.7 1521.59
    90.5 1523.07    95.2  1524.8     100  1526.1   103.6 1526.88   106.4 1527.59
   115.3 1530.03   120.9 1531.33   137.6 1534.37   143.3 1535.47   149.1 1536.71
#Mann= 3 ,-1,0
       0      .1       0    42.5    .045       0    56.6      .1       0
Bank Sta=42.5,56.6
XS Rating Curve= 0 ,0
Exp/Cntr(USF)=0,0
Exp/Cntr=0.3,0.1

Type RM Length L Ch R = 1 ,5975    ,96.4,95.2,94.1
XS GIS Cut Line= 3
2160157.26842584677486.2324965342160223.90852362677546.423552599
2160256.87029242677585.117802926
#Sta/Elev= 30
       0 1547.85     4.4 1543.85     9.3 1540.29    14.7 1536.75    15.5  1536.1
    21.1 1530.34      24 1528.03    25.5 1526.94    30.9 1523.46    34.2 1521.09
    35.3 1520.46    38.1 1519.12      41 1518.23    41.6 1518.12    46.2 1517.85
    52.4 1517.78    60.8 1518.19    63.6 1518.45    66.4 1518.93    69.3 1519.65
    72.1 1521.05    74.9 1522.63    77.8  1523.8    79.4 1524.34    86.3 1526.06
    93.4  1528.3    97.6 1529.47   128.8 1535.66   135.5  1536.8   140.6 1537.86
#Mann= 3 ,-1,0
       0      .1       0      41    .045       0    60.8      .1       0
Bank Sta=41,60.8
XS Rating Curve= 0 ,0
Exp/Cntr(USF)=0,0
Exp/Cntr=0.3,0.1

Type RM Length L Ch R = 1 ,5880    ,60.9,57.6,54.2
XS GIS Cut Line= 4
2160096.93740457677569.4110957452160117.57905617 677580.22338944
 2160165.7429099677617.5749494772160226.68492891677680.482840067
#Sta/Elev= 30
       0 1541.33     3.7 1540.63     8.2 1539.49    12.7 1536.73    16.7 1533.77
    21.7 1529.82    31.6 1521.17    34.4 1519.68    36.7 1519.01      421518.695
    51.9 1518.39    54.3 1518.45      57  1518.7    62.9 1519.49    67.1 1520.29
    72.1 1521.43    77.2 1523.03    82.9 1525.79    87.7 1528.31      97 1532.67
   100.4 1534.05     105 1535.39   110.7 1536.36   116.8 1537.05   122.2 1538.07
   128.1 1539.56   142.3 1542.54   156.4 1546.02   167.7 1548.38   171.8 1549.37
#Mann= 3 ,-1,0
       0      .1       0      42    .045       0      57      .1       0
Bank Sta=42,57
XS Rating Curve= 0 ,0
Exp/Cntr(USF)=0,0
Exp/Cntr=0.3,0.1

Type RM Length L Ch R = 1 ,5822    ,68.3,74.9,80.9
XS GIS Cut Line= 4
 2160062.5346519677616.5920136872160081.21043192677633.301922125
2160147.06712988677660.8241242582160193.26511203677701.124491666
#Sta/Elev= 30
       0 1537.52    12.9 1534.21    18.9 1532.48    23.7 1530.33    28.3 1527.59
    30.3 1526.52    32.6  1525.5    33.3 1525.25    36.9 1524.67    41.3 1523.42
    48.6 1518.52    49.9 1517.84    54.3 1517.35    58.6 1517.32      63 1517.37
    67.3 1517.72    71.6 1518.56      76 1519.61    80.3 1521.93    84.6 1524.99
      89 1527.58    93.3 1529.81      97 1531.56   103.2 1533.83   113.8 1536.08
   119.1 1537.52   125.8 1538.72   128.7 1539.35   137.2 1541.58   157.7 1546.09
#Mann= 3 ,-1,0
       0      .1       0    49.9    .045       0    67.3      .1       0
Bank Sta=49.9,67.3
XS Rating Curve= 0 ,0
Exp/Cntr(USF)=0,0
Exp/Cntr=0.3,0.1

Type RM Length L Ch R = 1 ,5747    ,63,63.5,63.8
XS GIS Cut Line= 3
 2160021.2513487677656.8923810962160132.32309303677763.049446465
2160164.75997411677795.486327551
#Sta/Elev= 30
       0 1536.22       4  1534.6    10.8 1532.78    17.8    1530    20.6 1529.58
    24.9 1529.26    27.7 1528.76    29.4 1528.29      39 1524.04    44.7    1522
    50.4 1520.69    59.4 1519.27    67.3 1517.68    75.7 1517.31    87.1 1517.41
      93 1517.73    98.5 1519.67   104.6 1523.03   112.6 1527.73   116.2 1529.46
     122 1531.25   125.8 1532.61   132.4 1535.33   150.9 1542.16   153.6 1543.02
   164.7 1545.98   170.4 1548.49   173.6 1549.72   180.5 1552.07   199.5 1558.95
#Mann= 3 ,-1,0
       0      .1       0    67.3    .045       0      93      .1       0
Bank Sta=67.3,93
XS Rating Curve= 0 ,0
Exp/Cntr(USF)=0,0
Exp/Cntr=0.3,0.1

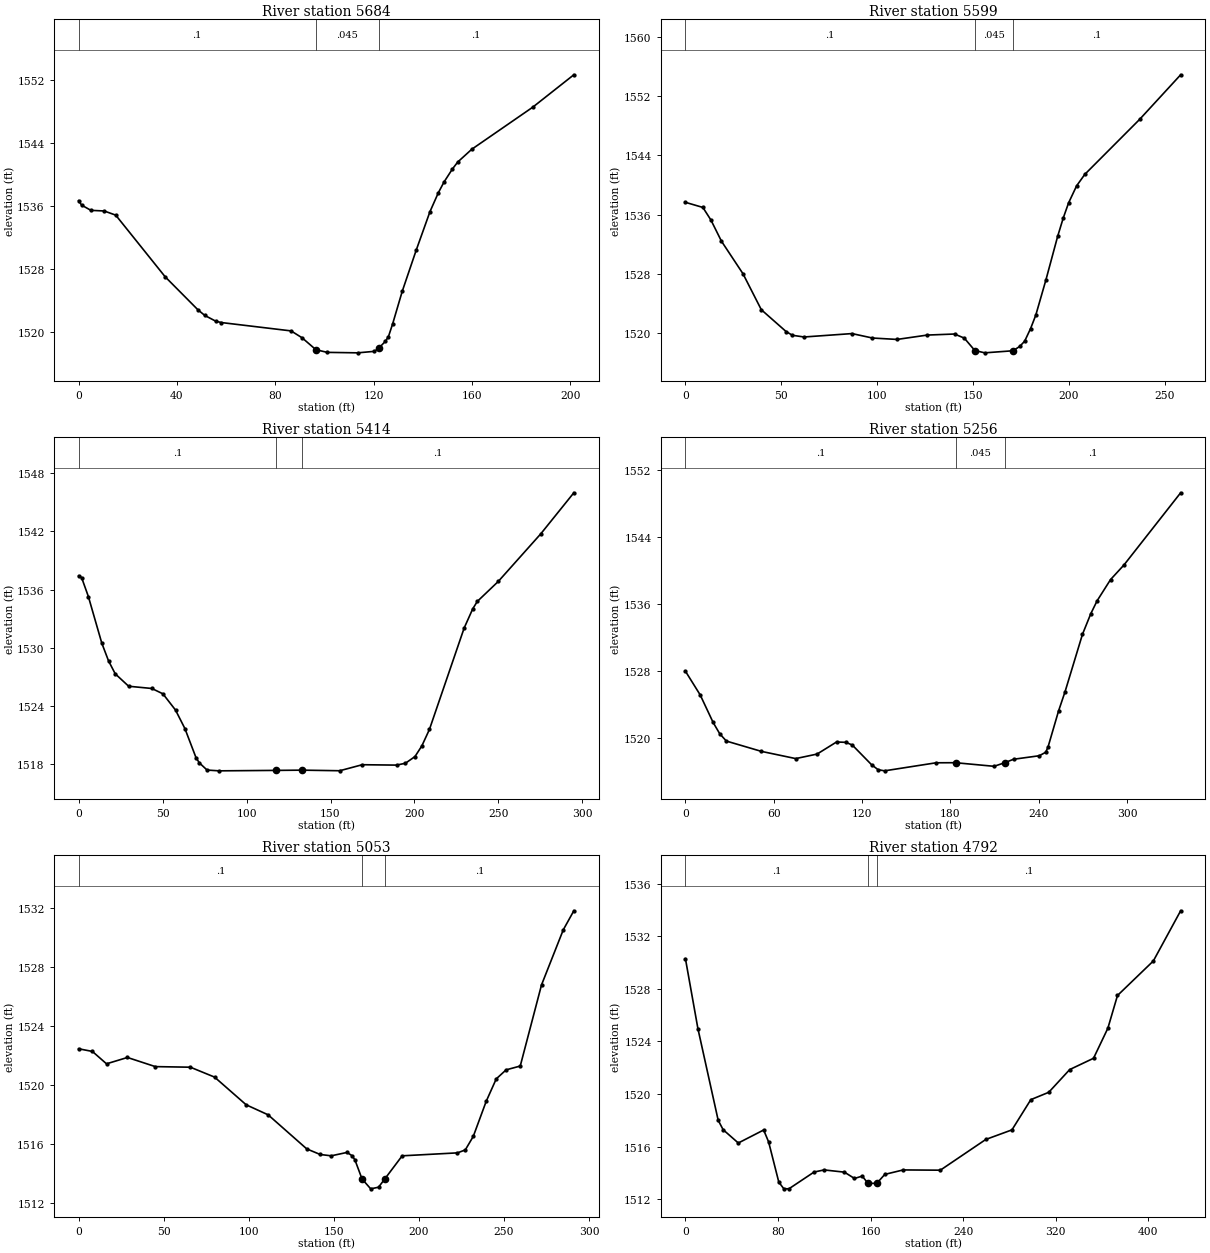
Type RM Length L Ch R = 1 ,5684    ,86.4,85.2,84.1
XS GIS Cut Line= 4
2159966.33460844677676.1605103532159984.02745267677706.631519857
2160071.50873802677794.1128052082160100.01387594677825.566750503
#Sta/Elev= 30
       0 1536.68     1.2 1536.12       5 1535.45    10.4 1535.37    15.1 1534.84
    35.2    1527    48.5 1522.81    51.3 1522.09    55.8 1521.35    58.1 1521.18
    86.4 1520.12    90.9 1519.24    96.5 1517.73   101.1 1517.39   113.5 1517.33
   120.3 1517.52     122  1517.9   124.8 1518.81     126 1519.39   127.7    1521
   131.6 1525.14   137.3 1530.39   142.9 1535.29   146.3 1537.69   148.6 1539.05
     152  1540.7   154.2  1541.6   159.9 1543.22   184.7 1548.57   201.4 1552.69
#Mann= 3 ,-1,0
       0      .1       0    96.5    .045       0     122      .1       0
Bank Sta=96.5,122
XS Rating Curve= 0 ,0
Exp/Cntr(USF)=0,0
Exp/Cntr=0.3,0.1

Type RM Length L Ch R = 1 ,5599    ,184.9,184.9,187.1
XS GIS Cut Line= 4
2159877.68286092677704.3996237182159888.64623184677742.448969873
2160011.82292872 677850.792870792160051.80698739677888.197312773
#Sta/Elev= 30
       0 1537.66     9.1 1536.97    13.3 1535.27    18.8 1532.41      30 1528.03
    39.6 1523.16    52.5 1520.22    55.8 1519.71    61.9 1519.48    86.9 1519.94
    97.6 1519.34   110.4 1519.15   126.2 1519.74   140.4 1519.88   145.5 1519.33
     1511517.654   156.2 1517.34   170.9 1517.62   174.4  1518.2     177 1518.91
   180.1 1520.62   182.8 1522.42   188.1 1527.19   194.2 1533.05   197.1 1535.51
   199.9 1537.57   204.1 1539.88   208.4 1541.44     237 1548.86   258.4 1554.88
#Mann= 3 ,-1,0
       0      .1       0     151    .045       0   170.9      .1       0
Bank Sta=151,170.9
XS Rating Curve= 0 ,0
Exp/Cntr(USF)=0,0
Exp/Cntr=0.3,0.1

Type RM Length L Ch R = 1 ,5414    ,146.6,158,151.1
XS GIS Cut Line= 4
2159734.95850221677743.3693347872159736.95553286677782.530971082
2159879.28954999677891.3875713072159939.73774206677938.261616695
#Sta/Elev= 30
       0 1537.42     1.8 1537.23     5.8 1535.29    13.8 1530.49    17.8 1528.67
    21.8 1527.33    29.8 1526.05    43.6 1525.82    50.2 1525.27    57.7  1523.6
    63.3 1521.69    69.9  1518.7    71.9 1518.16    76.5 1517.42    83.6 1517.34
   117.81517.386   133.21517.411   155.5 1517.35   168.9 1517.97   189.3 1517.93
   194.6 1518.12   200.3 1518.81   204.4 1519.91   208.9  1521.6   229.6 1532.05
   234.7 1534.02   237.4 1534.78   249.9 1536.84   275.2 1541.74   294.9 1545.97
#Mann= 3 ,-1,0
       0      .1       0   117.8    .045       0   133.2      .1       0
Bank Sta=117.8,133.2
XS Rating Curve= 0 ,0
Exp/Cntr(USF)=0,0
Exp/Cntr=0.3,0.1

Type RM Length L Ch R = 1 ,5256    ,188.8,202.8,199.9
XS GIS Cut Line= 5
2159635.54791493677828.3909216162159661.10424549677878.520646929
2159685.67764025677916.8551427572159857.69140358677993.524134413
2159899.95764257678012.199914431
#Sta/Elev= 30
       0 1528.02      10  1525.2    18.8 1521.91    23.3 1520.56    27.8 1519.69
    51.6 1518.46    74.9  1517.6    89.4 1518.14   102.6 1519.58   108.9 1519.54
   113.3 1519.22   126.4 1516.87   130.8 1516.28   135.2 1516.14   170.2  1517.1
   183.4 1517.11   209.6 1516.68   216.81517.107   222.8 1517.52   240.3 1517.94
   244.7 1518.36   246.3 1519.02   253.4 1523.29   257.8 1525.58   269.6 1532.41
   275.3 1534.89   279.6 1536.43   288.7 1538.95   297.8 1540.69   336.3  1549.3
#Mann= 3 ,-1,0
       0      .1       0   183.4    .045       0   216.8      .1       0
Bank Sta=183.4,216.8
XS Rating Curve= 0 ,0
Exp/Cntr(USF)=0,0
Exp/Cntr=0.3,0.1

Type RM Length L Ch R = 1 ,5053    ,259.7,260.9,258.6
XS GIS Cut Line= 4
 2159484.2457227678010.9412384552159588.14695043678035.304284957
2159719.99402562678112.6927856112159750.08955365678103.377503125
#Sta/Elev= 30
       0 1522.43     8.1 1522.25    16.4 1521.41    28.7 1521.84    45.1 1521.22
    65.7 1521.18    79.9 1520.51    98.5 1518.63   111.4 1517.95   134.1 1515.64
     142 1515.26   148.5 1515.17   157.8  1515.4   160.7 1515.18   162.4  1514.9
   166.6  1513.6   171.7 1512.93   176.3 1513.04   180.1 1513.62   190.2 1515.17
   222.7 1515.37   227.3 1515.57     232 1516.49   239.6 1518.87   245.5 1520.39
   251.3    1521   259.6 1521.26   272.1 1526.76   284.9  1530.5   291.1 1531.79
#Mann= 3 ,-1,0
       0      .1       0   166.6    .045       0   180.1      .1       0
Bank Sta=166.6,180.1
XS Rating Curve= 0 ,0
Exp/Cntr(USF)=0,0
Exp/Cntr=0.3,0.1

Type RM Length L Ch R = 1 ,4792    ,222.1,233.4,242.1
XS GIS Cut Line= 6
2159398.25849975678129.8902302012159449.13427333 678152.10359613
2159641.17240458678235.9411385062159670.55137243678269.619467494
2159745.79019251678288.9665926582159780.18508169678310.463398395
#Sta/Elev= 30
       0  1530.3    10.8 1524.97    28.3    1518    32.6 1517.28    45.7 1516.27
    67.6 1517.26    71.9 1516.35    80.7 1513.29      85 1512.79    89.4 1512.78
   111.2 1514.06   119.9 1514.22   137.4 1514.05   146.1 1513.57   152.8 1513.75
   157.81513.196   165.4  1513.2   172.3 1513.88   188.2 1514.22   220.3  1514.2
   259.6 1516.54   282.2 1517.27   298.5 1519.57     314 1520.13   332.1 1521.86
   352.7 1522.72   365.1 1525.01   373.4  1527.5   404.4 1530.13     428 1533.95
#Mann= 3 ,-1,0
       0      .1       0   157.8    .045       0   165.4      .1       0
Bank Sta=157.8,165.4
XS Rating Curve= 0 ,0
Exp/Cntr(USF)=0,0
Exp/Cntr=0.3,0.1

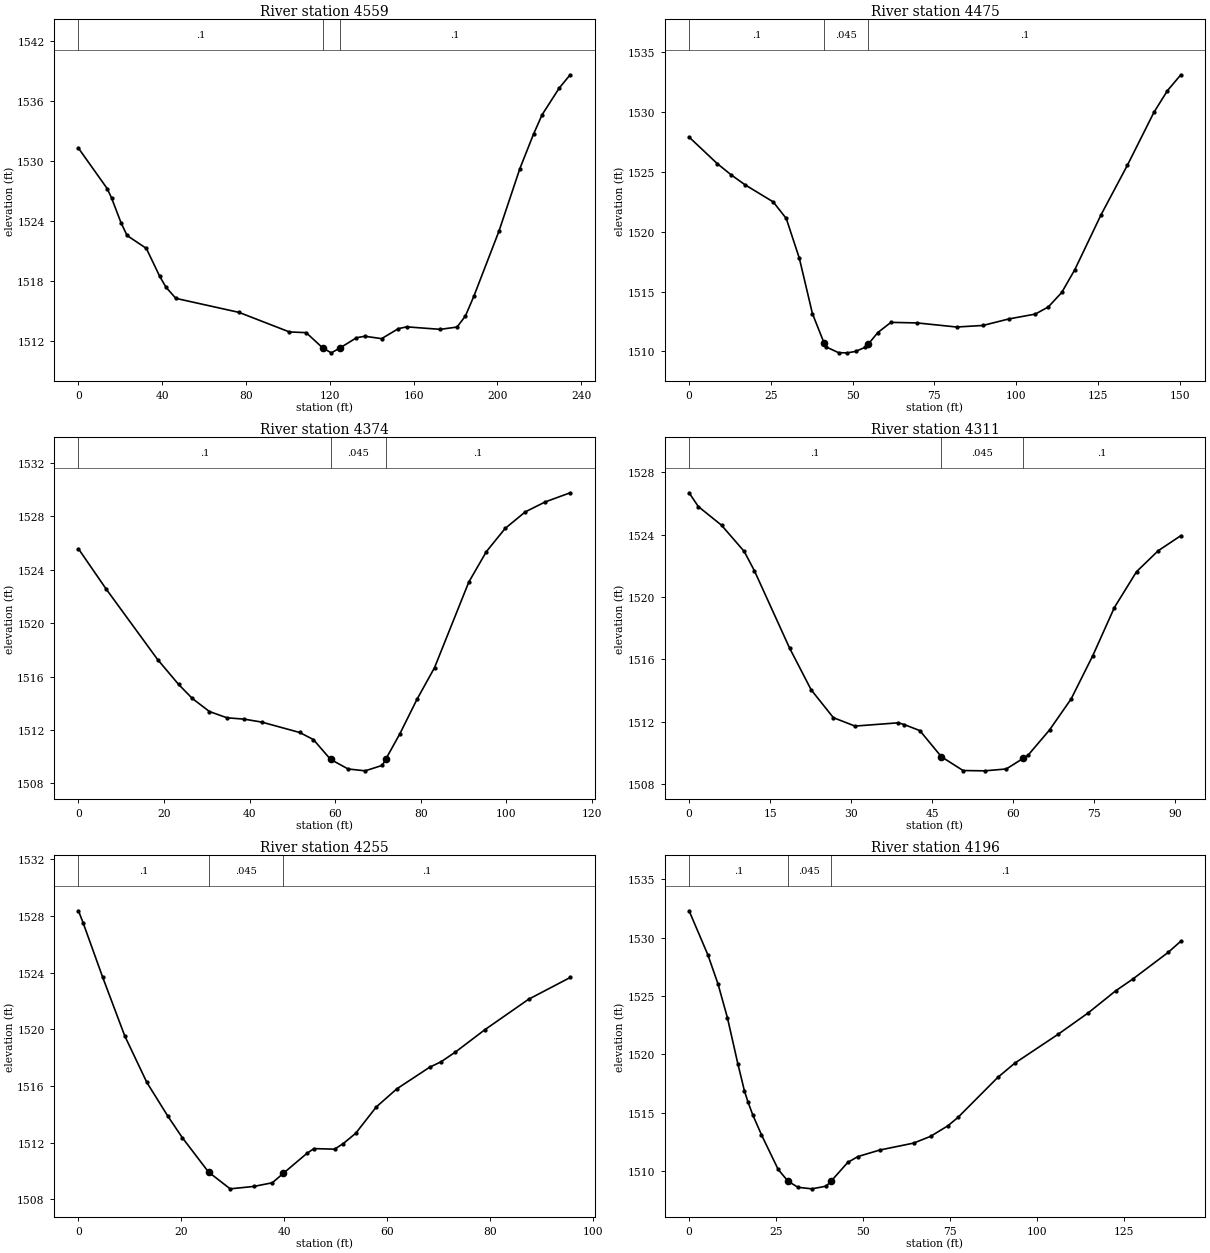
Type RM Length L Ch R = 1 ,4559    ,83.8,83.8,83.7
XS GIS Cut Line= 5
 2159384.4992702678168.9406905622159424.72194341678193.492192394
2159439.87074241678210.2081085362159444.04972145 678340.80120339
2159451.88530714678374.233035672
#Sta/Elev= 30
       0 1531.28    13.7 1527.24    15.8  1526.3    20.3 1523.83    23.2 1522.54
    32.4 1521.25    38.8 1518.45    41.8 1517.36    46.5 1516.25    76.6 1514.85
   100.7 1512.89   108.7 1512.82   116.7 1511.27   120.7  1510.8   124.7 1511.27
   132.7 1512.31   136.7 1512.46   144.7 1512.22   152.7 1513.22   156.7  1513.4
   172.7 1513.15   180.7 1513.38   184.7 1514.49   188.7 1516.45   200.7 1522.97
   210.7 1529.24   217.2 1532.68   221.3 1534.62   229.5  1537.3   234.7 1538.62
#Mann= 3 ,-1,0
       0      .1       0   116.7    .045       0   124.7      .1       0
Bank Sta=116.7,124.7
XS Rating Curve= 0 ,0
Exp/Cntr(USF)=0,0
Exp/Cntr=0.3,0.1

Type RM Length L Ch R = 1 ,4475    ,100.7,101.3,99.1
XS GIS Cut Line= 4
2159348.42798845678225.1402913932159357.36055614678248.647048466
2159363.47231298678346.4351578932159367.70352925678373.232860957
#Sta/Elev= 30
       0 1527.92     8.6  1525.7    12.9 1524.75    17.2 1523.91    25.7  1522.5
    29.7 1521.11    33.7 1517.78    37.7 1513.15    41.31510.666    41.7 1510.39
    45.7 1509.88    48.4 1509.87    50.9 1509.99    53.7 1510.32    54.7 1510.58
    57.7 1511.57    61.7 1512.42    69.8 1512.37    81.8 1512.03    89.8 1512.16
    97.8 1512.71   105.8 1513.11   109.8 1513.71   113.9 1514.92   117.9 1516.83
   125.9 1521.41     134 1525.58   142.1    1530   146.2  1531.8   150.3 1533.13
#Mann= 3 ,-1,0
       0      .1       0    41.3    .045       0    54.7      .1       0
Bank Sta=41.3,54.7
XS Rating Curve= 0 ,0
Exp/Cntr(USF)=0,0
Exp/Cntr=0.3,0.1

Type RM Length L Ch R = 1 ,4374    ,61.1,62.3,63.1
XS GIS Cut Line= 3
2159276.08422282678270.8432567592159289.66590468678366.959774572
2159299.06860751678382.108573575
#Sta/Elev= 25
       0 1525.56     6.4 1522.58    18.5 1517.27    23.4 1515.41    26.6 1514.36
    30.6 1513.38    34.7 1512.91    38.7 1512.81    42.8 1512.59    51.7 1511.81
    54.9 1511.28    58.9  1509.8      63 1509.08      67 1508.94      71 1509.35
    71.81509.809    75.1 1511.71    79.1 1514.29    83.2 1516.66    91.2 1523.06
    95.3 1525.34    99.7 1527.08   104.4 1528.32   109.1 1529.07   114.9 1529.75
#Mann= 3 ,-1,0
       0      .1       0    58.9    .045       0    71.8      .1       0
Bank Sta=58.9,71.8
XS Rating Curve= 0 ,0
Exp/Cntr(USF)=0,0
Exp/Cntr=0.3,0.1

Type RM Length L Ch R = 1 ,4311    ,58,56.7,55.3
XS GIS Cut Line= 4
2159216.01139918678287.5591729012159221.75749536678303.230344283
2159225.41410201678366.9597745722159226.45884677 678377.40722216
#Sta/Elev= 25
       0 1526.68     1.7  1525.8       6  1524.6    10.2 1522.92    12.1 1521.67
    18.6 1516.72    22.6 1514.04    26.7 1512.26    30.7 1511.72    38.7 1511.93
    39.8 1511.82    42.7 1511.43    46.7 1509.75    50.7 1508.87    54.7 1508.85
    58.7 1508.97    61.81509.644    62.7 1509.84    66.7 1511.47    70.7 1513.46
    74.7 1516.23    78.7 1519.32    82.8 1521.62    86.8 1522.96      91 1523.93
#Mann= 3 ,-1,0
       0      .1       0    46.7    .045       0    61.8      .1       0
Bank Sta=46.7,61.8
XS Rating Curve= 0 ,0
Exp/Cntr(USF)=0,0
Exp/Cntr=0.3,0.1

Type RM Length L Ch R = 1 ,4255    ,64,59,53.8
XS GIS Cut Line= 4
2159159.40171095678312.7620279472159164.10306237678324.776592674
2159172.46102044678373.8795963392159194.40066037678398.431098172
#Sta/Elev= 25
       0 1528.37      .9 1527.53     4.7 1523.69       9 1519.54    13.3 1516.25
    17.4 1513.86    20.2 1512.35    25.31509.922    29.5 1508.74    34.1 1508.91
    37.7 1509.17    39.81509.826    44.5 1511.27    45.8 1511.58    49.8 1511.54
    51.5 1511.94    53.9 1512.66    57.9 1514.52    61.9  1515.8    68.3 1517.33
    70.5 1517.71    73.3  1518.4      79 1519.97    87.5 1522.12    95.6 1523.66
#Mann= 3 ,-1,0
       0      .1       0    25.3    .045       0    39.8      .1       0
Bank Sta=25.3,39.8
XS Rating Curve= 0 ,0
Exp/Cntr(USF)=0,0
Exp/Cntr=0.3,0.1

Type RM Length L Ch R = 1 ,4196    ,73,72.4,72
XS GIS Cut Line= 3
2159097.76177018678344.1043707122159146.86477385678415.147014313
2159177.68474423678460.593411322
#Sta/Elev= 30
       0 1532.29     5.4 1528.52     8.3 1526.04      11 1523.16      14 1519.22
    15.9 1516.89    16.9 1515.96    18.3 1514.83    20.8 1513.13    25.6 1510.17
    28.4 1509.17    31.3 1508.64    35.3 1508.51    39.4 1508.74    40.81509.167
    45.6 1510.77    48.5 1511.27    54.8 1511.83    64.5 1512.42    69.4    1513
    74.4 1513.91    77.3 1514.63    88.7 1518.04    93.6 1519.26     106 1521.72
   114.7 1523.56   122.6 1525.45   127.5 1526.45   137.7 1528.74   141.3 1529.69
#Mann= 3 ,-1,0
       0      .1       0    28.4    .045       0    40.8      .1       0
Bank Sta=28.4,40.8
XS Rating Curve= 0 ,0
Exp/Cntr(USF)=0,0
Exp/Cntr=0.3,0.1

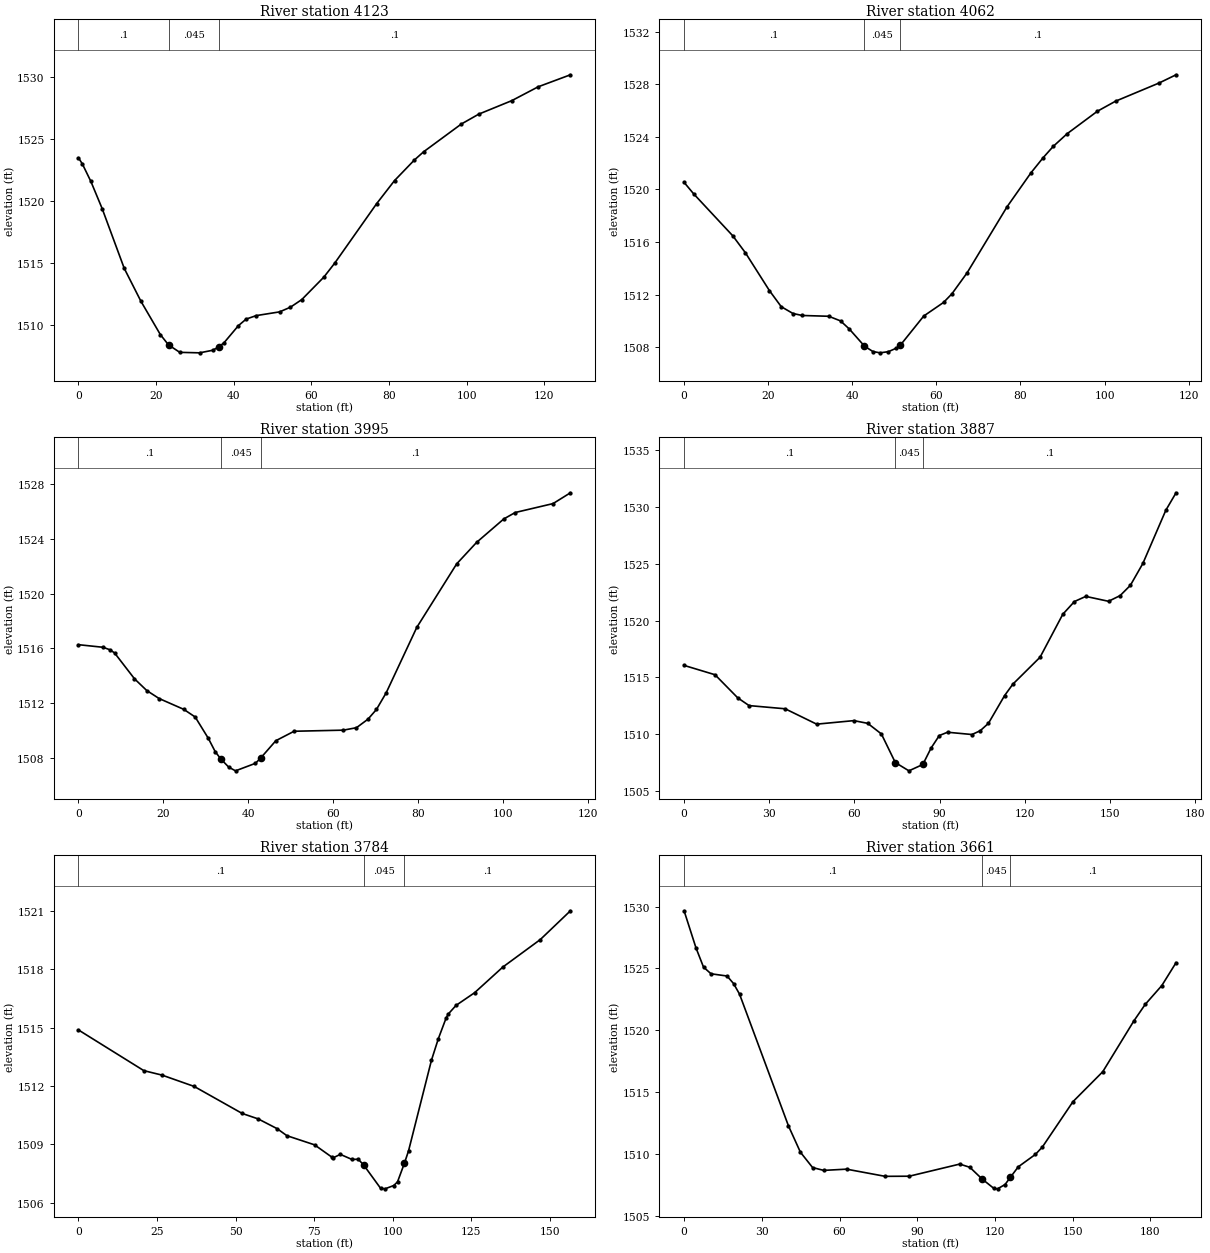
Type RM Length L Ch R = 1 ,4123    ,63.2,61,59.3
XS GIS Cut Line= 3
2159048.44467426678400.3622278872159094.93581602678461.479796279
2159125.23341403678501.180097114
#Sta/Elev= 30
       0 1523.47       1 1522.98     3.2 1521.56     6.1 1519.37    11.8 1514.53
    16.1 1511.87    21.1 1509.18    23.2 1508.35    26.1 1507.75    31.2 1507.71
    34.6 1507.92    36.2 1508.21    37.5 1508.53    41.2 1509.91    43.2 1510.44
    45.8 1510.72    51.8 1511.02    54.6  1511.4    57.5 1512.01    63.2 1513.83
      66 1514.96    76.8 1519.77    81.4 1521.63    86.5 1523.29    88.9 1523.96
    98.6  1526.2   103.1    1527   111.6 1528.09   118.4 1529.21   126.7 1530.18
#Mann= 3 ,-1,0
       0      .1       0    23.2    .045       0    36.2      .1       0
Bank Sta=23.2,36.2
XS Rating Curve= 0 ,0
Exp/Cntr(USF)=0,0
Exp/Cntr=0.3,0.1

Type RM Length L Ch R = 1 ,4062    ,65.1,66.9,68.8
XS GIS Cut Line= 4
2159004.25711427678438.1313990072159008.95846568678450.668336113
2159056.49435221678499.2489673992159076.86687501678528.501820646
#Sta/Elev= 30
       0 1520.53     2.3 1519.65    11.6 1516.46    14.6 1515.17    20.3  1512.3
    23.1 1511.08    25.9 1510.56    28.1 1510.41    34.4 1510.35    37.2    1510
    39.3 1509.38    42.9 1508.08    44.9 1507.67    46.6 1507.57    48.6 1507.66
    50.5 1507.93    51.4 1508.14      57 1510.37    61.7  1511.4    63.7 1512.06
    67.3 1513.65    76.8 1518.67    82.5 1521.26    85.4 1522.41    87.8 1523.27
    91.1 1524.23    98.3 1525.94   102.6  1526.7     113 1528.09     117 1528.71
#Mann= 3 ,-1,0
       0      .1       0    42.9    .045       0    51.4      .1       0
Bank Sta=42.9,51.4
XS Rating Curve= 0 ,0
Exp/Cntr(USF)=0,0
Exp/Cntr=0.3,0.1

Type RM Length L Ch R = 1 ,3995    ,108.1,108.4,107.7
XS GIS Cut Line= 3
2158953.04113383678474.0590104362158996.89461754 678542.41885268
2159014.95193436678572.084444598
#Sta/Elev= 30
       0 1516.27     5.8 1516.08     7.4  1515.9     8.5 1515.67    13.2 1513.78
    16.1 1512.92      19 1512.34    24.8 1511.55    27.5 1510.99    30.6 1509.43
    32.2 1508.47    33.5 1507.94    35.4 1507.33      37 1507.06    41.7 1507.61
    42.91507.986    46.5 1509.26    50.8 1509.95    62.4 1510.03    65.5 1510.21
    68.2 1510.83    70.2 1511.54    72.5 1512.76    79.7 1517.53    89.1 1522.17
    93.8 1523.74   100.2 1525.45   102.9 1525.92   111.8 1526.57   115.9 1527.36
#Mann= 3 ,-1,0
       0      .1       0    33.5    .045       0    42.9      .1       0
Bank Sta=33.5,42.9
XS Rating Curve= 0 ,0
Exp/Cntr(USF)=0,0
Exp/Cntr=0.3,0.1

Type RM Length L Ch R = 1 ,3887    ,102.8,102.5,101
XS GIS Cut Line= 4
2158873.01946768678506.3230925012158870.63093371678538.170212112
2158922.38250307678613.8071211872158971.74553847678619.380367119
#Sta/Elev= 30
       0 1516.06    10.9 1515.24    18.9 1513.21    22.9 1512.53    35.6 1512.25
    46.7  1510.9    59.8 1511.21    64.7 1510.97    69.5 1510.04    74.4 1507.53
    79.2  1506.8    84.1 1507.36      87  1508.8    89.9  1509.9    92.8 1510.19
   101.4 1509.99   104.3 1510.32   107.2 1510.97   112.9 1513.41   115.8 1514.41
   125.4 1516.78   133.4 1520.55   137.5 1521.67   141.5 1522.12   149.5 1521.69
   153.6 1522.19   157.2 1523.09   161.6 1525.01   169.7 1529.69   173.3 1531.22
#Mann= 3 ,-1,0
       0      .1       0    74.4    .045       0    84.1      .1       0
Bank Sta=74.4,84.1
XS Rating Curve= 0 ,0
Exp/Cntr(USF)=0,0
Exp/Cntr=0.3,0.1

Type RM Length L Ch R = 1 ,3784    ,125.6,123.3,119.4
XS GIS Cut Line= 4
2158776.89883202678575.4028369192158796.24595718678602.632124186
2158855.72045306 678668.555661782158886.53254128678683.603425796
#Sta/Elev= 30
       0 1514.88    20.8 1512.79    26.6 1512.56    36.8 1511.98    52.1 1510.59
    57.2 1510.31    63.2 1509.81    66.3 1509.45    75.1 1508.98    80.5 1508.36
    81.1 1508.32    83.3 1508.49      87 1508.23      89 1508.24    90.7 1507.95
    96.1 1506.75    97.5 1506.72   100.3 1506.89   101.5 1507.08   103.71508.041
     105 1508.67   112.3 1513.33   114.5 1514.44   116.9 1515.47   117.6 1515.69
   120.1 1516.14     126 1516.79     135 1518.11   146.9 1519.52   156.5    1521
#Mann= 3 ,-1,0
       0      .1       0    90.7    .045       0   103.7      .1       0
Bank Sta=90.7,103.7
XS Rating Curve= 0 ,0
Exp/Cntr(USF)=0,0
Exp/Cntr=0.3,0.1

Type RM Length L Ch R = 1 ,3661    ,106.7,104.2,103
XS GIS Cut Line= 4
2158654.36703932 678668.555661782158678.01352563678684.319985988
2158791.23003584678752.393204156 2158811.2937212678773.890009893
#Sta/Elev= 30
       0 1529.66     4.6 1526.66     7.5 1525.11    10.4 1524.57    16.6 1524.39
    19.1 1523.78    21.4 1522.93    40.3 1512.28    44.9 1510.16    49.6 1508.92
    53.9 1508.69    62.7 1508.79    77.6 1508.21    86.9 1508.22   106.4  1509.2
   110.3 1508.94     115    1508   119.6 1507.23     121  1507.2   123.9 1507.55
   125.9 1508.12     129 1508.98   135.6 1509.98   138.3 1510.58   150.1 1514.24
   161.6 1516.66   173.6 1520.76     178  1522.1   184.4 1523.62   189.9 1525.47
#Mann= 3 ,-1,0
       0      .1       0     115    .045       0   125.9      .1       0
Bank Sta=115,125.9
XS Rating Curve= 0 ,0
Exp/Cntr(USF)=0,0
Exp/Cntr=0.3,0.1