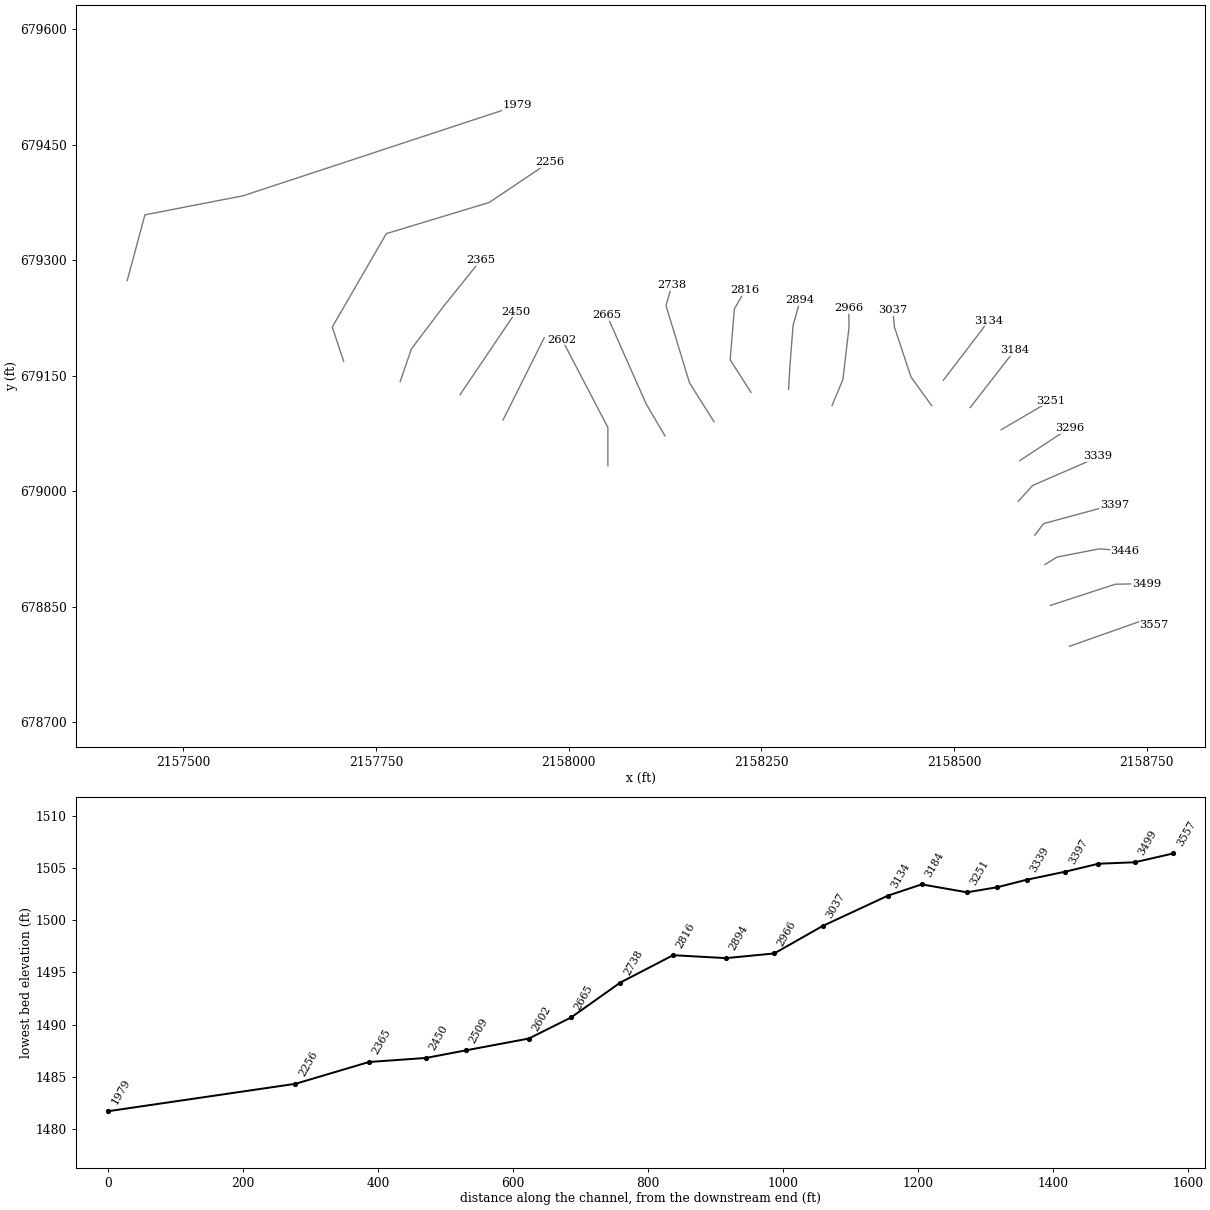
HEC-RAS study LFFRENCHCK.prj: LFFRENCHCK

--- LFFRENCHCK.g01 (geometry) --- (continued)

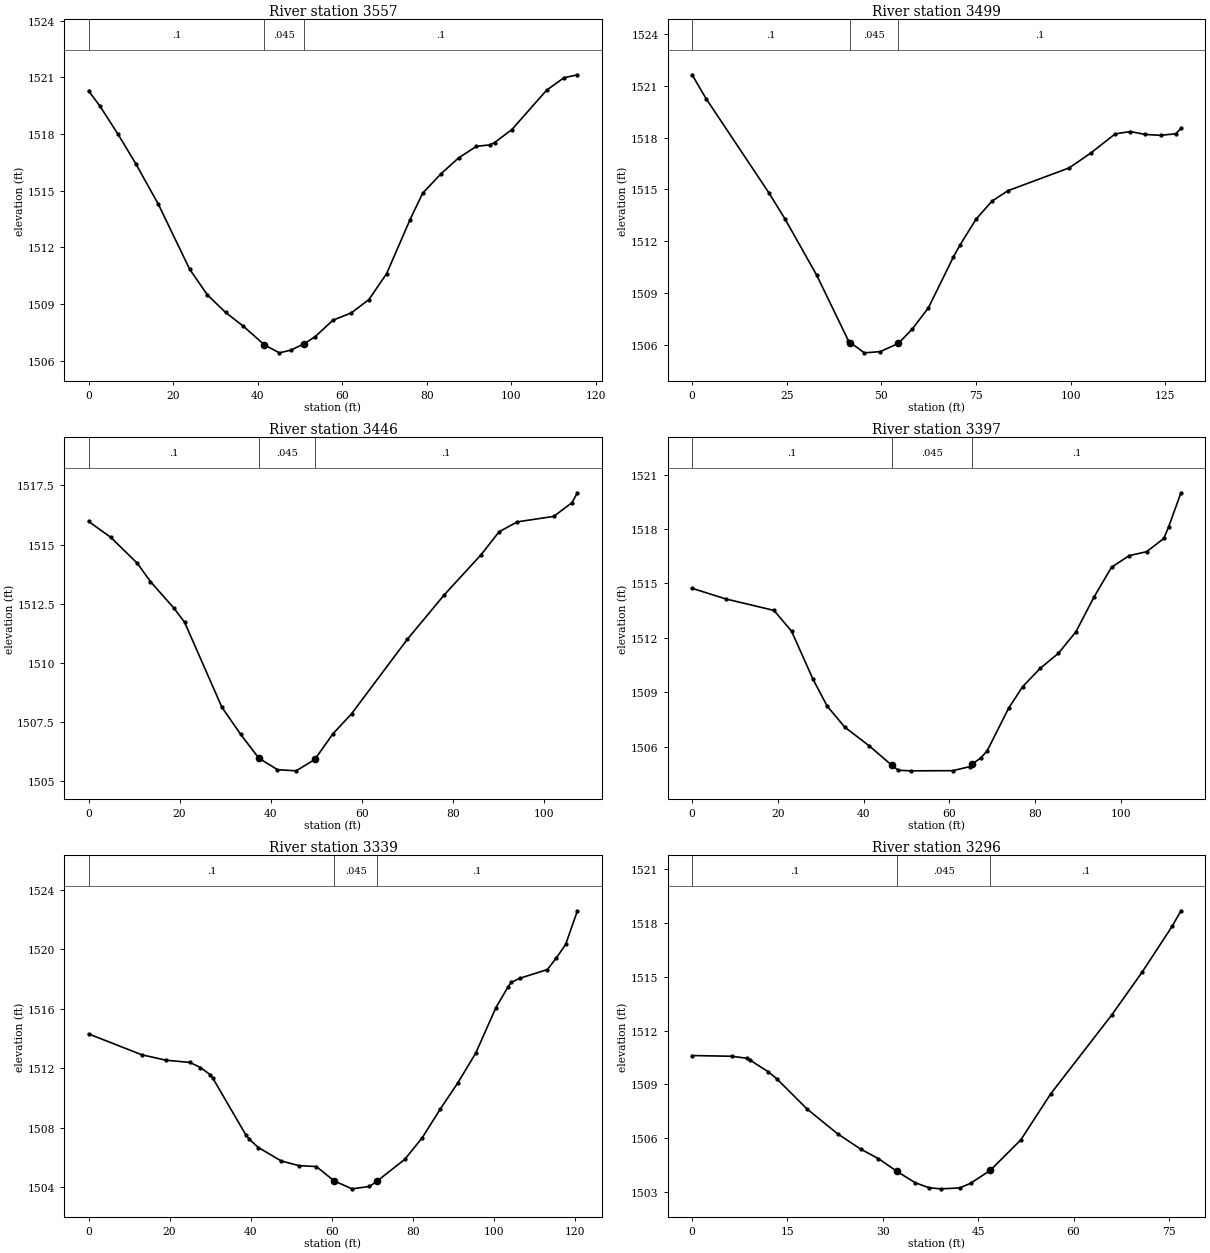
Type RM Length L Ch R = 1 ,3557    ,57.8,57.3,57
XS GIS Cut Line= 3
2158649.65955174678798.6835409262158739.89305731678830.530660537
2158759.35518596 678826.10744948
#Sta/Elev= 29
       0 1520.28     2.7 1519.47     6.9 1518.01    11.2 1516.41    16.5 1514.28
    23.9 1510.84    28.1 1509.48    32.4 1508.55    36.6 1507.82    41.6 1506.83
    45.1 1506.41    47.8 1506.55      51 1506.89    53.6 1507.27    57.8 1508.14
    62.1 1508.52    66.3 1509.23    70.5 1510.61      76 1513.45      79 1514.86
    83.3 1515.88    87.5 1516.73    91.7 1517.34    94.9 1517.42      96 1517.54
   100.1 1518.23   108.3 1520.31   112.4 1520.97   115.6 1521.13
#Mann= 3 ,-1,0
       0      .1       0    41.6    .045       0      51      .1       0
Bank Sta=41.6,51
XS Rating Curve= 0 ,0
Exp/Cntr(USF)=0,0
Exp/Cntr=0.3,0.1

Type RM Length L Ch R = 1 ,3499    ,55.5,53.8,52.7
XS GIS Cut Line= 3
2158624.88956983678851.7620736112158708.93057991678879.185982164
2158749.62412163678880.070624376
#Sta/Elev= 25
       0 1521.63     3.7 1520.25    20.3  1514.8    24.5 1513.31    32.9 1510.05
    41.3 1506.25    41.8 1506.15    45.5 1505.56    49.7 1505.63    54.5 1506.11
    58.2 1506.95    62.4 1508.16      69  1511.1    70.8 1511.81      75 1513.29
    79.2 1514.33    83.4 1514.93    99.6 1516.25   105.3 1517.11   111.7 1518.21
   115.7 1518.35   119.7 1518.18   123.7 1518.13   127.7 1518.22   129.1 1518.53
#Mann= 3 ,-1,0
       0      .1       0    41.8    .045       0    54.5      .1       0
Bank Sta=41.8,54.5
XS Rating Curve= 0 ,0
Exp/Cntr(USF)=0,0
Exp/Cntr=0.3,0.1

Type RM Length L Ch R = 1 ,3446    ,47.6,49,50.3
XS GIS Cut Line= 4
2158617.81243213678904.8406062952158633.73599194678914.571670621
2158688.58380905678925.1873771582158721.31557087678922.533450523
#Sta/Elev= 22
       0 1515.98     4.9  1515.3    10.7 1514.21    13.6 1513.43    18.7 1512.32
    21.1 1511.71    29.3 1508.11    33.4 1506.97    37.4 1505.96    41.5 1505.47
    45.6 1505.42    49.7  1505.9    53.7 1506.99    57.8 1507.84      70 1510.98
    78.1 1512.86    86.2 1514.56    90.2 1515.54    94.2 1515.96   102.2 1516.19
   106.2 1516.77   107.4 1517.19
#Mann= 3 ,-1,0
       0      .1       0    37.4    .045       0    49.7      .1       0
Bank Sta=37.4,49.7
XS Rating Curve= 0 ,0
Exp/Cntr(USF)=0,0
Exp/Cntr=0.3,0.1

Type RM Length L Ch R = 1 ,3397    ,55.9,57.5,58.8
XS GIS Cut Line= 4
2158604.54279896678942.8802213862158616.04314771 678957.91913898
2158687.69916684678977.381267631 2158708.0459377678981.804478688
#Sta/Elev= 28
       0 1514.73     7.9 1514.14    19.1 1513.51    23.2 1512.36    28.2 1509.71
    31.5 1508.23    35.6 1507.07    41.3 1506.04    46.6 1504.96    48.1 1504.69
      51 1504.66    60.8 1504.67    64.7 1504.89    65.31505.028    67.3 1505.37
    68.8 1505.76    73.8 1508.11    77.1 1509.31    81.2 1510.32    85.4 1511.14
    89.5 1512.33    93.7 1514.24    97.8 1515.89   101.9 1516.53     106 1516.75
     110 1517.48   111.1 1518.11     114    1520
#Mann= 3 ,-1,0
       0      .1       0    46.6    .045       0    65.3      .1       0
Bank Sta=46.6,65.3
XS Rating Curve= 0 ,0
Exp/Cntr(USF)=0,0
Exp/Cntr=0.3,0.1

Type RM Length L Ch R = 1 ,3339    ,41.1,43.2,45.1
XS GIS Cut Line= 4
2158583.31138589678987.1123319562158601.88887233679007.459102819
2158670.89096482679037.5369380072158686.81452462679045.498717909
#Sta/Elev= 30
       0  1514.3    13.1  1512.9    19.1 1512.53      25 1512.38    27.6 1512.04
      30 1511.56    30.6 1511.35    38.8 1507.51    39.7  1507.2    41.9 1506.66
    47.5 1505.76    51.9 1505.44    56.2 1505.38    60.6 1504.41      65 1503.88
    69.3 1504.04    71.21504.405      78 1505.86    82.3 1507.31    86.8 1509.26
    91.1 1511.01    95.5    1513   100.5 1516.07   103.5 1517.47   104.3 1517.77
   106.5 1518.05   113.2 1518.63   115.4 1519.41   117.7 1520.32   120.6 1522.58
#Mann= 3 ,-1,0
       0      .1       0    60.6    .045       0    71.2      .1       0
Bank Sta=60.6,71.2
XS Rating Curve= 0 ,0
Exp/Cntr(USF)=0,0
Exp/Cntr=0.3,0.1

Type RM Length L Ch R = 1 ,3296    ,45.7,44.9,44.1
XS GIS Cut Line= 2
2158585.02994077679039.6752512452158649.28174344679081.987413978
#Sta/Elev= 23
       0 1510.61     6.2 1510.57     8.6 1510.46     9.1 1510.36      12  1509.7
    13.3 1509.32    18.1 1507.62    22.9 1506.24    26.5 1505.39    29.3 1504.86
    32.2 1504.15    35.1 1503.51    37.3 1503.23    39.1 1503.17    42.1 1503.22
    43.8 1503.48    46.9  1504.2    51.7  1505.9    56.4 1508.47      66 1512.87
    70.8 1515.27    75.5 1517.82    76.9 1518.69
#Mann= 3 ,-1,0
       0      .1       0    32.2    .045       0    46.9      .1       0
Bank Sta=32.2,46.9
XS Rating Curve= 0 ,0
Exp/Cntr(USF)=0,0
Exp/Cntr=0.3,0.1

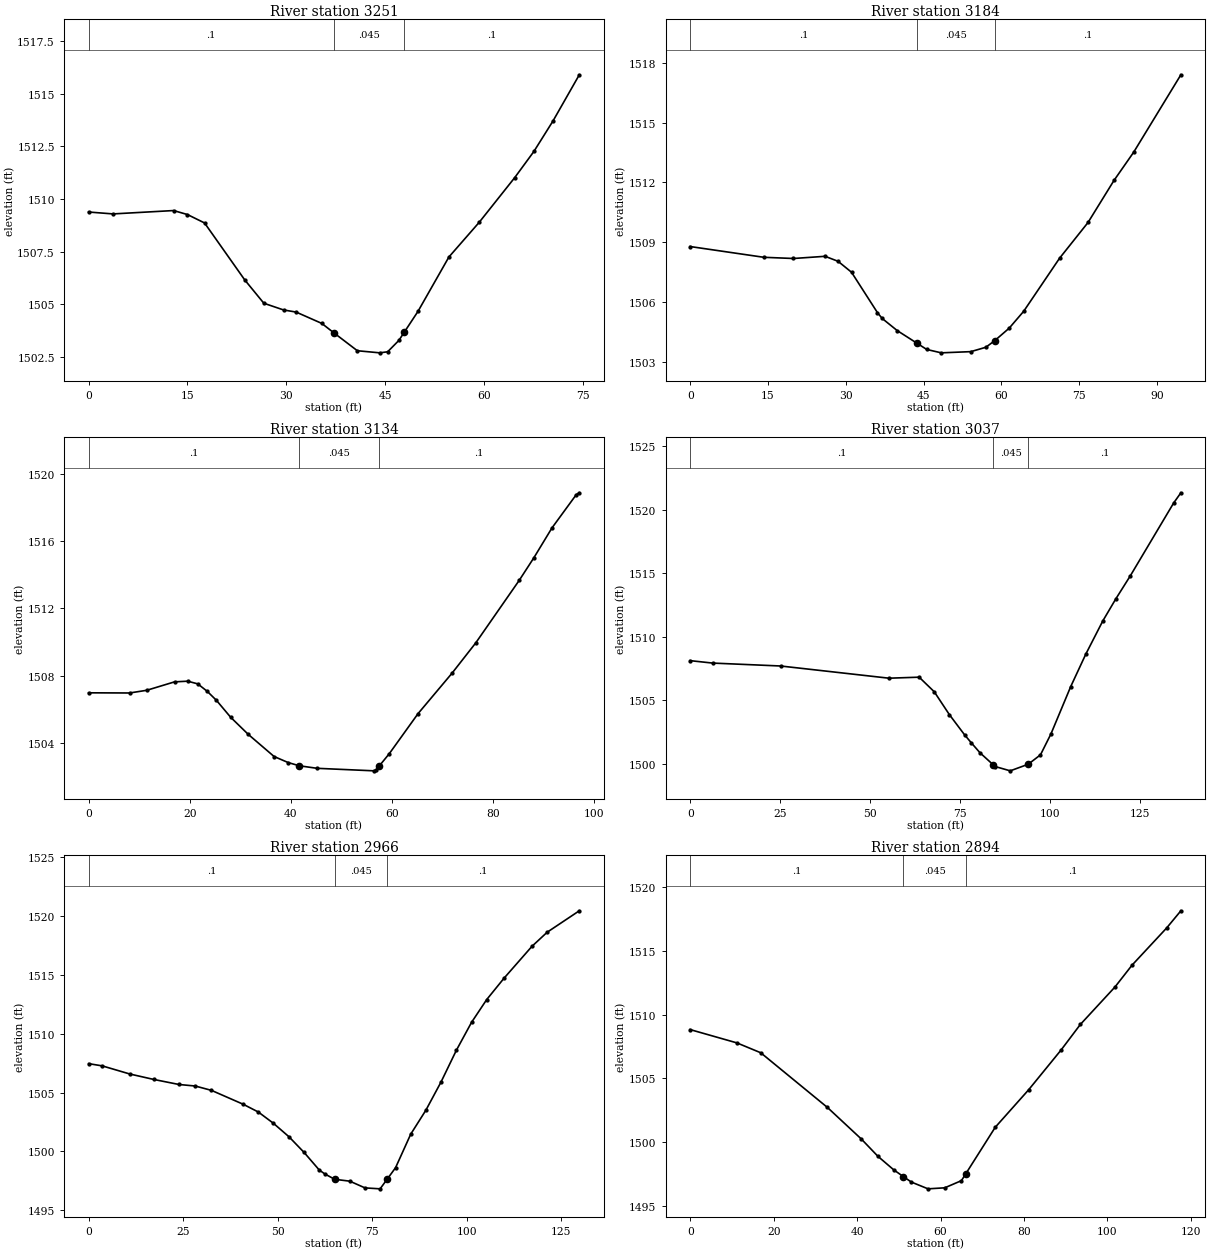
Type RM Length L Ch R = 1 ,3251    ,62.6,67.2,71
XS GIS Cut Line= 2
2158561.00081132 679079.897924462158625.25261399679117.508735778
#Sta/Elev= 23
       0 1509.38     3.7 1509.29    12.9 1509.45      15 1509.26    17.6 1508.86
    23.7 1506.15    26.6 1505.04    29.6 1504.72    31.5 1504.62    35.4 1504.08
    37.2 1503.64    40.8 1502.78    44.2 1502.68    45.4 1502.73    47.1 1503.27
    47.91503.651      50 1504.65    54.7 1507.24    59.3 1508.89    64.7 1511.02
    67.6 1512.26    70.5 1513.71    74.5 1515.91
#Mann= 3 ,-1,0
       0      .1       0    37.2    .045       0    47.9      .1       0
Bank Sta=37.2,47.9
XS Rating Curve= 0 ,0
Exp/Cntr(USF)=0,0
Exp/Cntr=0.3,0.1

Type RM Length L Ch R = 1 ,3184    ,49.8,50,50.1
XS GIS Cut Line= 2
 2158520.7781381679108.6284053282158578.76147222679183.327655584
#Sta/Elev= 22
       0 1508.78    14.2 1508.24    19.9 1508.18      26 1508.29    28.5 1508.04
    31.1 1507.49    36.1 1505.46      37 1505.17    39.9 1504.56    43.8 1503.91
    45.6 1503.61    48.4 1503.44    54.1  1503.5      57 1503.72    58.7 1504.05
    61.5 1504.68    64.3 1505.53    71.2 1508.19    76.7 1509.99    81.7  1512.1
    85.5 1513.52    94.6 1517.41
#Mann= 3 ,-1,0
       0      .1       0    43.8    .045       0    58.7      .1       0
Bank Sta=43.8,58.7
XS Rating Curve= 0 ,0
Exp/Cntr(USF)=0,0
Exp/Cntr=0.3,0.1

Type RM Length L Ch R = 1 ,3134    ,84.6,96.7,107.7
XS GIS Cut Line= 3
2158485.88092334679144.0512946272158536.18538348679209.870214434
2158544.17768089679221.623592971
#Sta/Elev= 26
       0 1506.99     8.1 1506.98    11.5 1507.14      17 1507.64    19.6 1507.68
    21.6 1507.52    23.5 1507.07    25.3 1506.54    28.1 1505.54    31.6 1504.52
    36.7 1503.21    39.5 1502.85    41.7 1502.66    45.2 1502.51    56.5 1502.36
    56.8 1502.39    57.51502.647    59.5 1503.38    65.2 1505.76    71.9 1508.15
    76.6 1509.95    85.2 1513.66    88.1    1515    91.7 1516.78    96.5 1518.75
    97.1 1518.86
#Mann= 3 ,-1,0
       0      .1       0    41.7    .045       0    57.5      .1       0
Bank Sta=41.7,57.5
XS Rating Curve= 0 ,0
Exp/Cntr(USF)=0,0
Exp/Cntr=0.3,0.1

Type RM Length L Ch R = 1 ,3037    ,77.1,71.6,67.5
XS GIS Cut Line= 4
2158470.83659882679111.1418347242158444.03889575679148.282510901
2158422.41267924679213.6312955662158420.53213868679235.257512073
#Sta/Elev= 23
       0 1508.12     6.2 1507.93    25.1  1507.7    55.2 1506.74    63.6 1506.82
    67.8 1505.67      72 1503.87    76.2 1502.29    78.1 1501.65    80.5 1500.87
    84.11499.944    84.7 1499.79    88.9 1499.45    93.9 1499.97    97.3 1500.71
   100.2 1502.35   105.7 1506.08   109.9 1508.64   114.6 1511.24   118.2 1512.97
   122.2 1514.77   134.3 1520.53   136.3 1521.33
#Mann= 3 ,-1,0
       0      .1       0    84.1    .045       0    93.9      .1       0
Bank Sta=84.1,93.9
XS Rating Curve= 0 ,0
Exp/Cntr(USF)=0,0
Exp/Cntr=0.3,0.1

Type RM Length L Ch R = 1 ,2966    ,70.9,71.4,71.9
XS GIS Cut Line= 4
2158341.54943491679111.1418347242158355.65348916 679144.99156491
2158363.64578656679213.1611604242158363.17565142679237.608187781
#Sta/Elev= 30
       0 1507.45     3.6 1507.26    10.9 1506.57    17.2 1506.11    23.9 1505.68
    28.2 1505.55    32.5 1505.18    40.9    1504    44.9 1503.34    48.9 1502.38
      53 1501.24      57 1499.91      61 1498.42    62.5 1498.08    65.1 1497.63
    69.1 1497.47    73.1  1496.9    77.1 1496.82      791497.651    81.2 1498.62
    85.2 1501.46    89.2 1503.49    93.2 1505.88    97.3  1508.6   101.3 1510.96
   105.3 1512.89   109.9 1514.71   117.3 1517.42   121.3 1518.61   129.8 1520.43
#Mann= 3 ,-1,0
       0      .1       0    65.1    .045       0      79      .1       0
Bank Sta=65.1,79
XS Rating Curve= 0 ,0
Exp/Cntr(USF)=0,0
Exp/Cntr=0.3,0.1

Type RM Length L Ch R = 1 ,2894    ,78.6,78.5,78.3
XS GIS Cut Line= 4
2158285.23188827679132.3037202282158286.97312954679163.065649238
2158291.03602582 679215.30288718 2158300.3226459679248.386471209
#Sta/Elev= 21
       0 1508.82    11.2 1507.78    16.9 1507.01    32.9 1502.73      41 1500.27
      45 1498.91    48.8 1497.85    51.11497.325      53  1496.9      57 1496.37
      61 1496.45      65 1497.01      661497.522    73.1 1501.18    81.1 1504.11
    88.9 1507.23    93.5 1509.22   101.8 1512.15   105.9 1513.86   114.2 1516.77
   117.6 1518.11
#Mann= 3 ,-1,0
       0      .1       0    51.1    .045       0      66      .1       0
Bank Sta=51.1,66
XS Rating Curve= 0 ,0
Exp/Cntr(USF)=0,0
Exp/Cntr=0.3,0.1

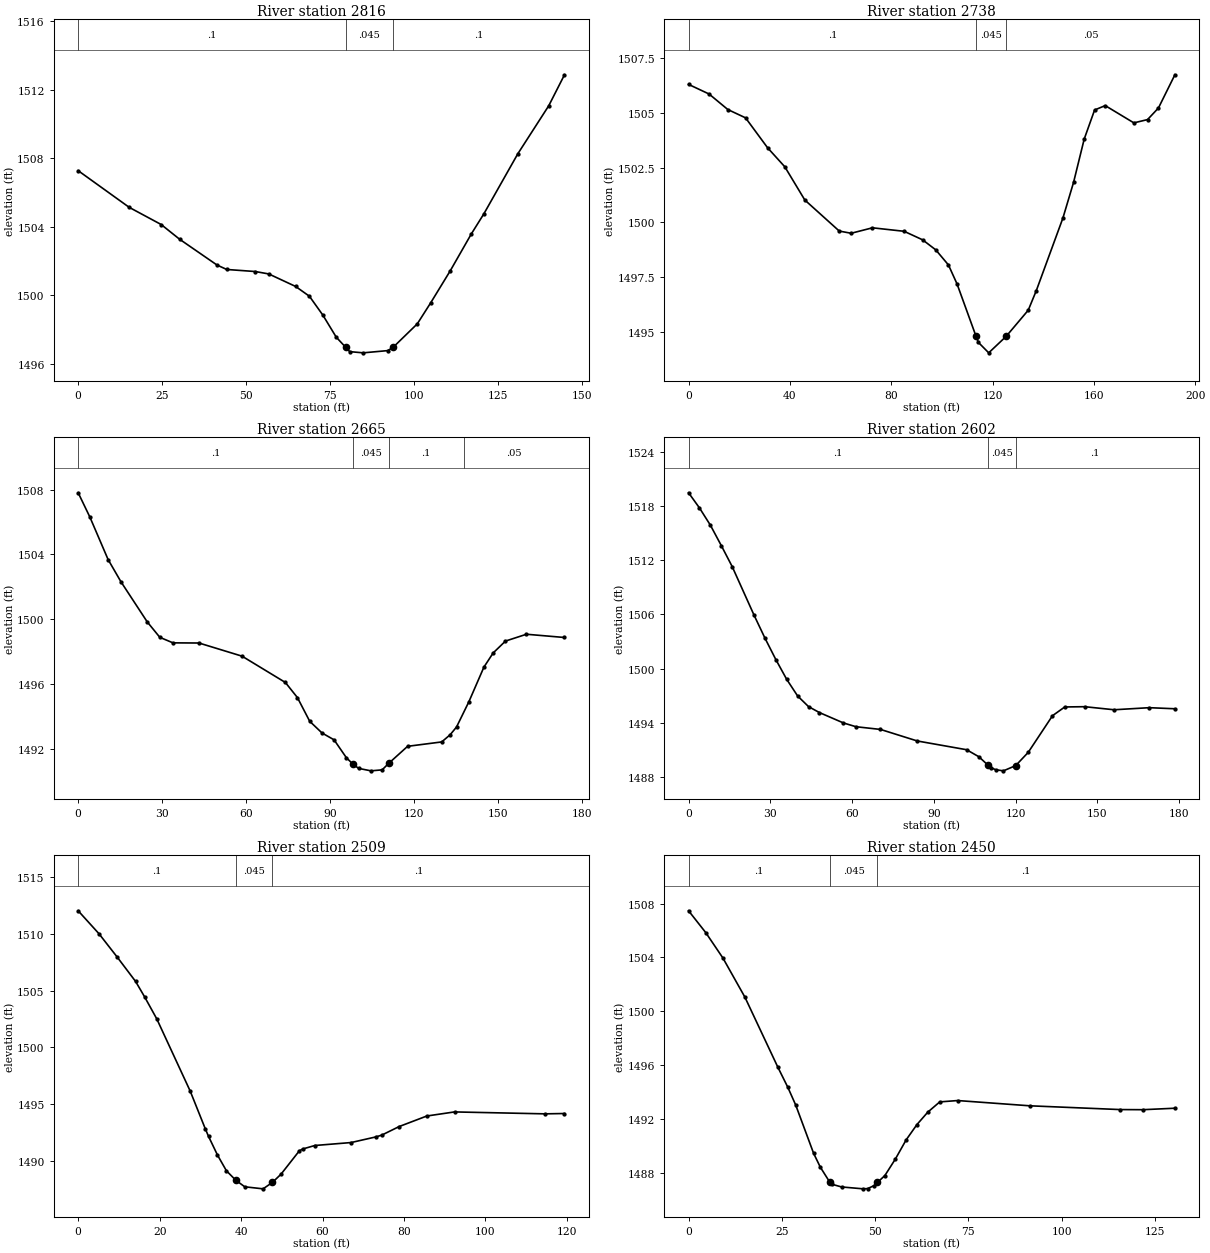
Type RM Length L Ch R = 1 ,2816    ,73.3,78,81.9
XS GIS Cut Line= 4
2158236.48061534679128.4114655882158209.40083119679170.723628321
2158214.90141235679236.7306021832158228.86442605679261.271656568
#Sta/Elev= 25
       0 1507.27    15.2 1505.13    24.7 1504.13    30.2 1503.27    41.3 1501.77
    44.2 1501.51    52.7 1501.39    56.7 1501.25    64.7 1500.52    68.8 1499.95
    72.8 1498.85    76.8 1497.56    79.61496.972    80.8 1496.72    84.8 1496.65
    92.1 1496.78    93.7 1496.97   100.9 1498.34   104.9 1499.57   110.7 1501.43
     117 1503.59   120.7 1504.75   130.8 1508.25     140 1511.05   144.7 1512.86
#Mann= 3 ,-1,0
       0      .1       0    79.6    .045       0    93.7      .1       0
Bank Sta=79.6,93.7
XS Rating Curve= 0 ,0
Exp/Cntr(USF)=0,0
Exp/Cntr=0.3,0.1

Type RM Length L Ch R = 1 ,2738    ,70.9,73.1,73.8
XS GIS Cut Line= 4
2158188.42629035679090.357153671 2158156.6921683679140.708627323
2158126.22741114679240.9884529992158133.84360043 679267.64511552
#Sta/Elev= 30
       0 1506.31     8.1 1505.87    15.5 1505.16    22.5 1504.78    31.2 1503.41
      38 1502.54    45.9 1501.02    59.5  1499.6    64.2  1499.5    72.6 1499.75
    85.1 1499.59    92.4  1499.2    97.6 1498.74   102.6 1498.05     106 1497.18
   113.51494.784   114.4 1494.51   118.5 1494.03   125.41494.786   134.1 1495.98
   137.3 1496.88   147.8  1500.2     152 1501.83   156.2 1503.81   160.3 1505.14
   164.5 1505.34   175.8 1504.55   181.2  1504.7   185.5 1505.23     192 1506.75
#Mann= 3 ,-1,0
       0      .1       0   113.5    .045       0   125.4     .05       0
Bank Sta=113.5,125.4
XS Rating Curve= 0 ,0
Exp/Cntr(USF)=0,0
Exp/Cntr=0.3,0.1

Type RM Length L Ch R = 1 ,2665    ,61.8,62.5,63
XS GIS Cut Line= 3
2158124.78216987679071.9694136212158100.51215035679113.228446801
2158049.54510937679228.511039508
#Sta/Elev= 30
       0  1507.8     4.2  1506.3    10.7 1503.69    15.3 1502.32    24.7 1499.85
    29.2  1498.9    33.9 1498.56    43.2 1498.55    58.6 1497.74    74.1 1496.12
    78.4 1495.19    82.8 1493.73    87.2 1493.01    91.5 1492.59    95.9 1491.49
    98.2  1491.1   100.3 1490.83   104.7 1490.68   108.7 1490.74     1111491.134
   117.8 1492.19     130 1492.46     133  1492.9   135.3 1493.38   139.7 1494.93
   145.1 1497.07   148.4 1497.94   152.8 1498.67   160.3 1499.09   173.9 1498.89
#Mann= 4 ,-1,0
       0      .1       0    98.2    .045       0     111      .1       0
  137.87     .05       0
Bank Sta=98.2,111
XS Rating Curve= 0 ,0
Exp/Cntr(USF)=0,0
Exp/Cntr=0.3,0.1

Type RM Length L Ch R = 1 ,2602    ,102.7,93.1,84.4
XS GIS Cut Line= 3
2158050.75861034679033.1373823932158050.75861034679082.890922404
2157991.29706253679196.960014136
#Sta/Elev= 30
       0 1519.48       4  1517.8       8 1515.89      12 1513.63      16  1511.3
      24 1505.93      28 1503.38      32    1501      36  1498.8      40 1496.96
      44 1495.78      48 1495.12    56.8 1493.97    61.4 1493.55    70.4 1493.25
    83.9 1491.97     102    1491   106.5 1490.22   109.7 1489.33     111    1489
   112.7 1488.78   115.5 1488.66     120 1489.24   124.6 1490.71   133.5 1494.77
     138 1495.74   145.3 1495.77   156.1 1495.43     169 1495.66   178.4 1495.54
#Mann= 3 ,-1,0
       0      .1       0   109.7    .045       0     120      .1       0
Bank Sta=109.7,120
XS Rating Curve= 0 ,0
Exp/Cntr(USF)=0,0
Exp/Cntr=0.3,0.1

Type RM Length L Ch R = 1 ,2509    ,60.6,59.1,57.9
XS GIS Cut Line= 2
2157914.84650105679092.5989302112157968.24054398679199.387016087
#Sta/Elev= 27
       0 1512.04     5.1 1510.02     9.6 1507.95    14.1 1505.81    16.3 1504.46
    19.3 1502.51    27.5 1496.15    31.2 1492.83      32 1492.16    34.2 1490.51
    36.4 1489.12    38.7 1488.29    40.9 1487.71    45.4 1487.53    47.7  1488.1
    49.8 1488.82    54.3 1490.88    55.1 1491.04    58.1 1491.35      67 1491.61
      73  1492.1    74.5 1492.26    78.8 1493.02    85.6 1493.95    92.4 1494.31
   114.6 1494.14   119.4 1494.17
#Mann= 3 ,-1,0
       0      .1       0    38.7    .045       0    47.7      .1       0
Bank Sta=38.7,47.7
XS Rating Curve= 0 ,0
Exp/Cntr(USF)=0,0
Exp/Cntr=0.3,0.1

Type RM Length L Ch R = 1 ,2450    ,85.2,84.6,84.2
XS GIS Cut Line= 2
2157859.02545616679125.3634565592157931.83551471679233.365043412
#Sta/Elev= 27
       0 1507.46     4.6 1505.84     9.2 1503.95    15.1 1501.04    23.9 1495.85
    26.6 1494.34    28.7 1493.03    33.5 1489.44    35.3 1488.41    37.8 1487.31
    38.4 1487.14      41 1486.94    46.8  1486.8      48 1486.82    49.7 1487.04
    50.61487.273    52.6 1487.79    55.4 1489.01    58.3 1490.44    61.2 1491.58
    64.1  1492.5    67.3 1493.26    72.1 1493.36    91.4 1492.97   115.6 1492.69
   121.7 1492.68   130.3 1492.79
#Mann= 3 ,-1,0
       0      .1       0    37.8    .045       0    50.6      .1       0
Bank Sta=37.8,50.6
XS Rating Curve= 0 ,0
Exp/Cntr(USF)=0,0
Exp/Cntr=0.3,0.1

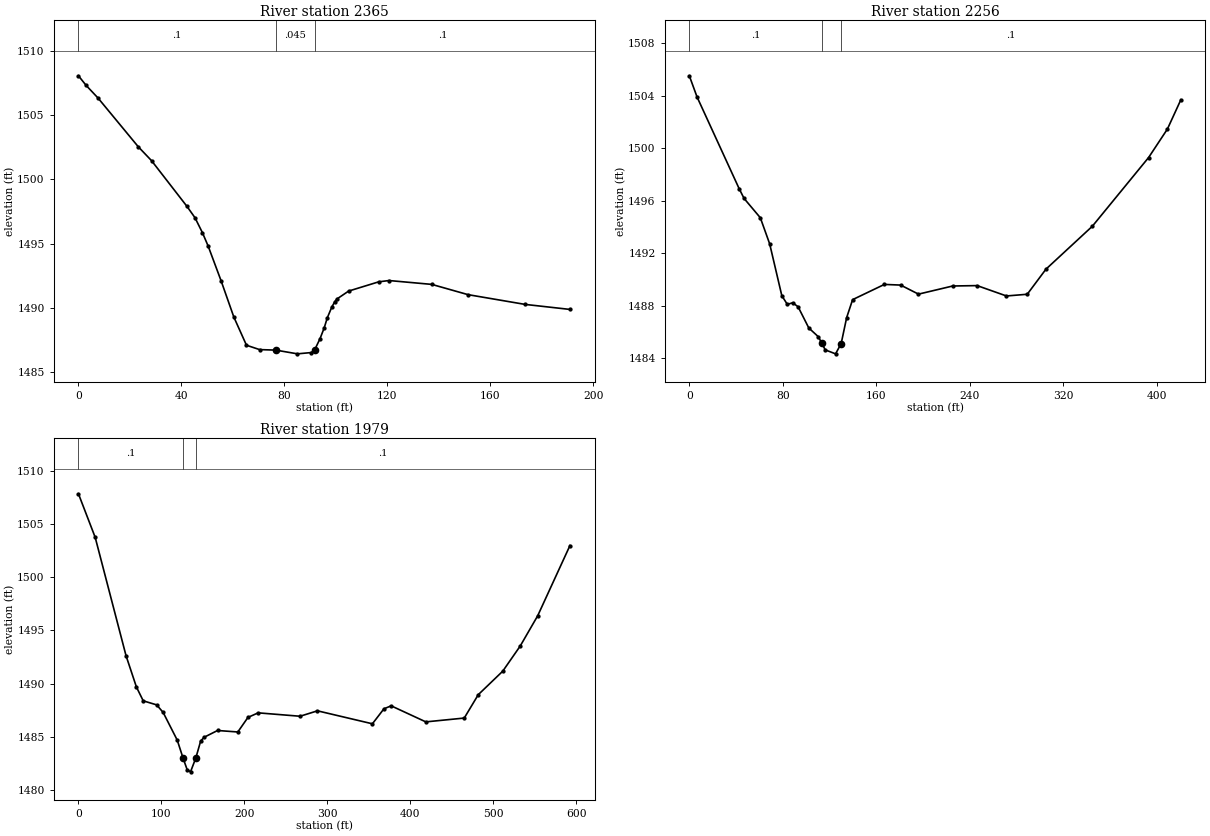
Type RM Length L Ch R = 1 ,2365    ,107.6,108.9,110.6
XS GIS Cut Line= 4
 2157781.3613937679142.3524702212157795.92340541679184.825004377
2157837.18243859679239.4325482912157885.72247763679300.107597084
#Sta/Elev= 30
       0 1508.07       3 1507.32     7.6 1506.34    23.3 1502.53    28.4 1501.46
    42.2 1497.89    45.3 1497.01    48.2 1495.84    50.4 1494.81    55.4 1492.12
    60.4 1489.27    65.3 1487.08    70.4 1486.74    76.7  1486.7    85.1 1486.41
    90.5 1486.51    91.8 1486.72    93.9  1487.6    95.5 1488.43    96.7 1489.21
    98.4 1490.03    99.6 1490.47   100.5 1490.69     105  1491.3   116.7 1492.02
   120.7 1492.12   137.3 1491.82   151.4 1491.02   173.6 1490.26     191 1489.87
#Mann= 3 ,-1,0
       0      .1       0    76.7    .045       0    91.8      .1       0
Bank Sta=76.7,91.8
XS Rating Curve= 0 ,0
Exp/Cntr(USF)=0,0
Exp/Cntr=0.3,0.1

Type RM Length L Ch R = 1 ,2256    ,287.5,277.8,265.6
XS GIS Cut Line= 5
 2157708.0661937679168.690305759 2157693.2345151679213.185341541
2157763.34790482679334.5354391282157896.83301217679374.985471657
2157975.03640839679427.570513945
#Sta/Elev= 30
       0 1505.51     6.6  1503.9    42.7  1496.9    46.9 1496.16    60.8 1494.69
    68.8  1492.7    79.2 1488.75    83.9 1488.09    88.5 1488.21    93.1 1487.91
   102.3 1486.29   110.5 1485.62   113.5 1485.11   116.4 1484.62   125.2 1484.32
     130  1485.1   134.7 1487.08   139.8 1488.45     167 1489.61   180.9 1489.56
   196.2 1488.87   225.5 1489.49   246.4 1489.52   271.5 1488.73   289.3 1488.86
   305.3 1490.77     345 1494.04   393.2 1499.28   409.3 1501.45   420.8 1503.68
#Mann= 3 ,-1,0
       0      .1       0   113.5    .045       0     130      .1       0
Bank Sta=113.5,130
XS Rating Curve= 0 ,0
Exp/Cntr(USF)=0,0
Exp/Cntr=0.3,0.1

Type RM Length L Ch R = 1 ,1979    ,466.2,465,463.2
XS GIS Cut Line= 4
2157427.30154474679273.7137200872157450.21188191679358.940174369
2157577.59335659679383.6833385152157933.16178951679500.984264839
#Sta/Elev= 30
       0 1507.85    20.2 1503.75    57.4 1492.61    69.9 1489.67    78.1 1488.37
    94.3 1487.99   102.1 1487.28   119.1 1484.67     126 1483.01     131  1481.9
   135.1 1481.69  141.51    1483   147.3 1484.58   151.4 1484.94   167.7 1485.58
   192.1 1485.44   204.3 1486.81   216.6 1487.24   267.1 1486.92   288.1 1487.43
   354.3 1486.21   368.2 1487.62   376.9  1487.9   418.7 1486.39     465 1486.75
   481.9 1488.95   511.4 1491.16   532.4 1493.52   553.5 1496.37   592.4 1502.98
#Mann= 3 ,0,0
       0      .1       0     126    .045       0  141.51      .1       0
Bank Sta=126,141.51
XS Rating Curve= 0 ,0
Exp/Cntr(USF)=0,0
Exp/Cntr=0.3,0.1