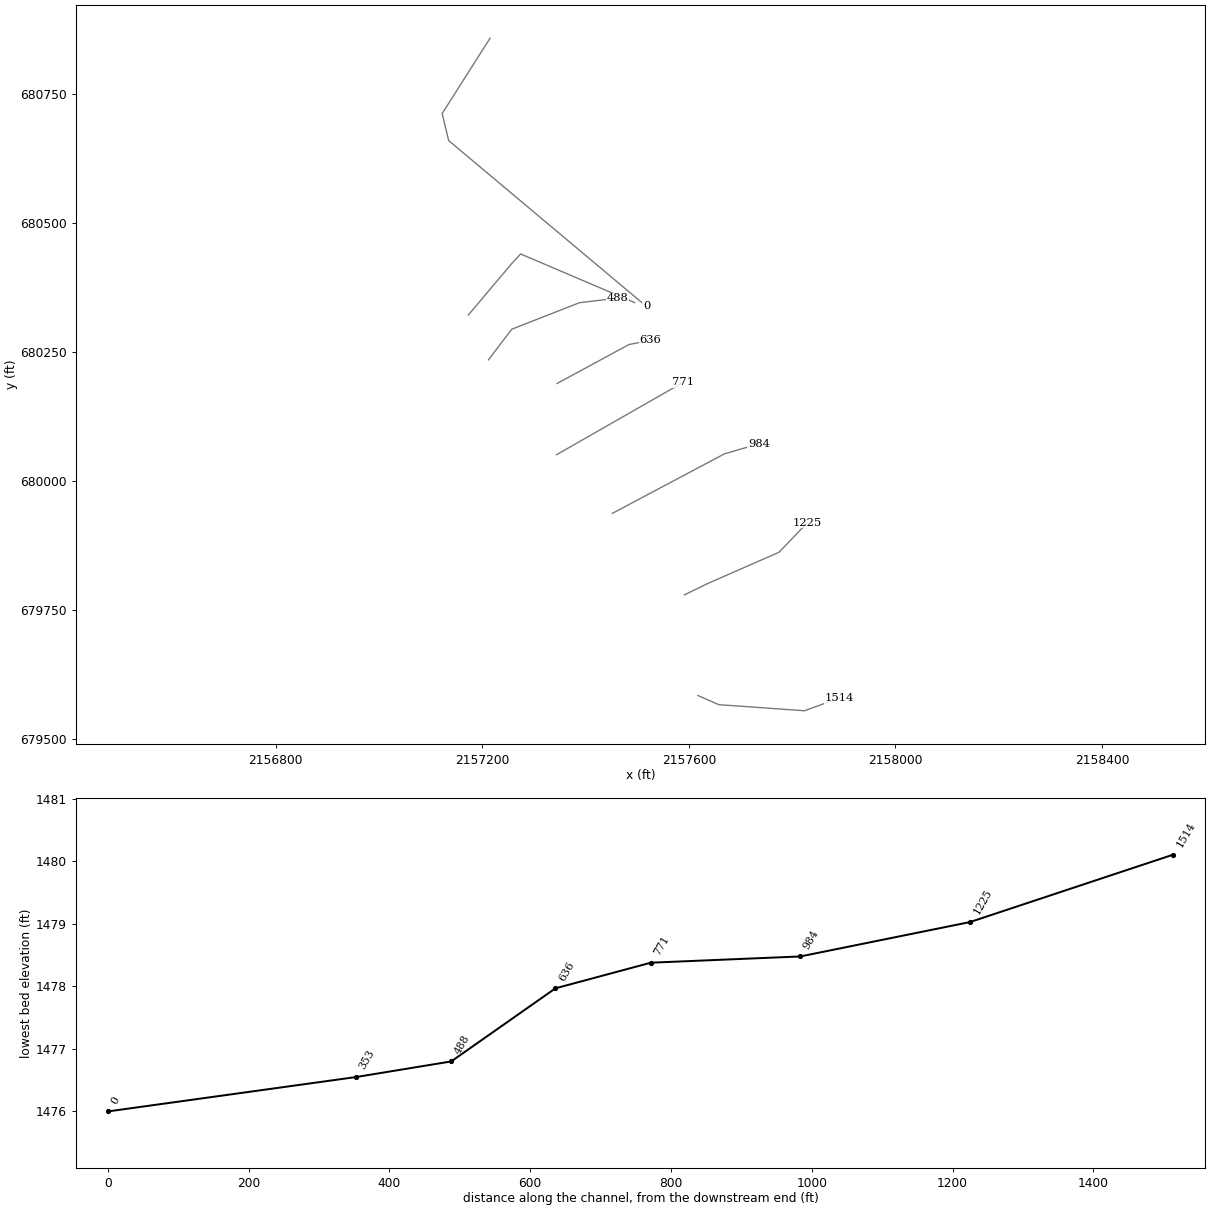
HEC-RAS study LFFRENCHCK.prj: LFFRENCHCK

--- LFFRENCHCK.g01 (geometry) --- (continued)

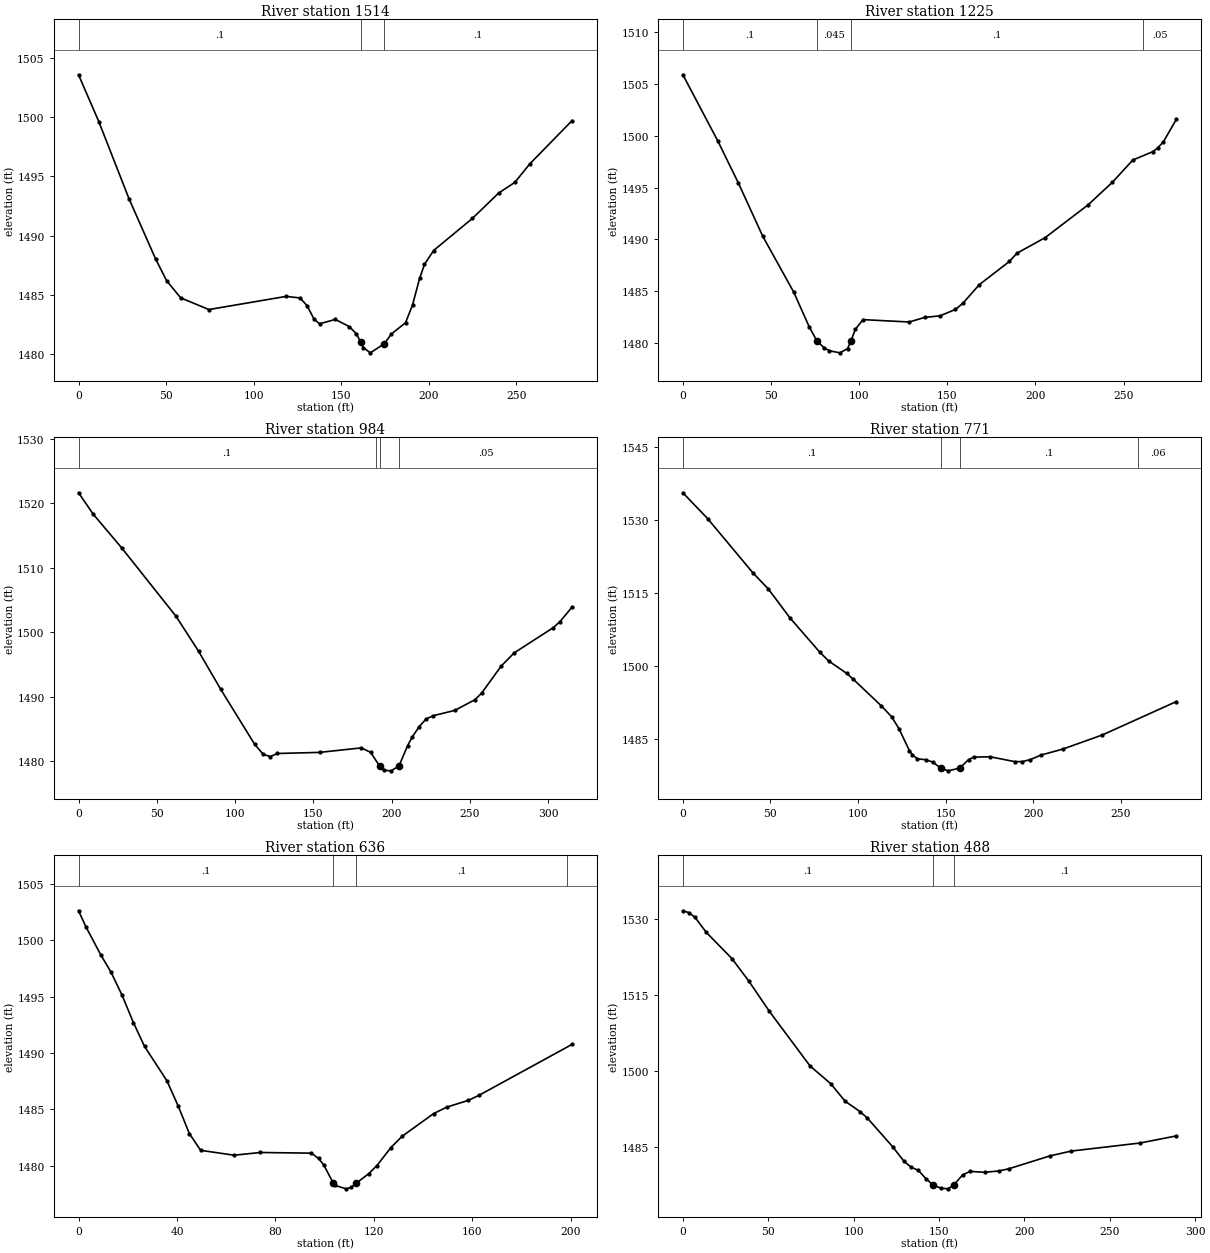
Type RM Length L Ch R = 1 ,1514    ,282.6,289,293.9
XS GIS Cut Line= 4
2157617.59376328679584.5593823582157657.89413068 679566.86653813
2157824.01027927679555.0713086452157890.84991302679579.644703406
#Sta/Elev= 30
       0 1503.56    11.6  1499.6    28.8 1493.11      44 1488.03    50.3 1486.19
    58.3 1484.75    74.4 1483.76   118.5 1484.87   126.5 1484.74   130.5 1484.08
   134.5 1482.94   137.6 1482.56   146.6 1482.93   154.6 1482.32   158.6 1481.72
     1611481.036   162.6 1480.55   166.6 1480.11   174.6 1480.88   178.6  1481.7
   186.7 1482.65   190.7 1484.16   194.7 1486.38   197.5 1487.57   202.7 1488.74
   224.8 1491.44   239.8 1493.58   249.1 1494.49   257.6 1496.04   281.8  1499.7
#Mann= 3 ,-1,0
       0      .1       0     161    .045       0   174.6      .1       0
Bank Sta=161,174.6
XS Rating Curve= 0 ,0
Exp/Cntr(USF)=0,0
Exp/Cntr=0.3,0.1

Type RM Length L Ch R = 1 ,1225    ,241,241,239.9
XS GIS Cut Line= 4
2157591.42124389679779.461521933   2157636.32078679801.304539499
2157774.65989125679861.9795882922157829.26743517679919.014134158
#Sta/Elev= 30
       0  1505.9    19.8 1499.51    31.4 1495.47    45.3  1490.3    62.9 1484.89
    71.6 1481.57      76 1480.19    80.1 1479.52    83.1 1479.23    89.1 1479.03
    93.4 1479.44    95.3 1480.16    97.8  1481.3   102.2 1482.24   128.4 1482.01
   137.1 1482.45   145.9 1482.61   154.6 1483.22     159 1483.85   168.1 1485.61
   185.2 1487.86   189.5 1488.66   205.4 1490.15   229.8 1493.32   243.7 1495.52
   255.2 1497.66   266.6 1498.47   269.4 1498.84   272.6 1499.43     280 1501.62
#Mann= 4 ,-1,0
       0      .1       0      76    .045       0    95.3      .1       0
  260.99     .05       0
Bank Sta=76,95.3
XS Rating Curve= 0 ,0
Exp/Cntr(USF)=0,0
Exp/Cntr=0.3,0.1

Type RM Length L Ch R = 1 ,984     ,211.4,212.3,213.1
XS GIS Cut Line= 3
2157451.86863167679937.2166487962157669.08530635680052.499241504
2157735.82786002680071.915257118
#Sta/Elev= 30
       0 1521.59     9.4 1518.27    27.5 1513.07    62.3 1502.44    76.7 1497.02
    90.9  1491.1   112.6 1482.57   118.1 1481.02   122.6  1480.7   127.1 1481.17
     154 1481.34   180.7 1482.04   186.6 1481.35   192.5 1479.19   195.1 1478.58
   199.6 1478.48   204.7  1479.2   210.2 1482.35   213.2 1483.72   217.7 1485.34
   222.1 1486.53   226.8 1487.04   240.4 1487.85   253.3 1489.51   257.5 1490.51
     270  1494.7   278.3 1496.76   303.3 1500.67   307.5 1501.59   315.4 1503.87
#Mann= 4 ,-1,0
       0      .1       0     190     .05       0   192.5    .045       0
   204.7     .05       0
Bank Sta=192.5,204.7
XS Rating Curve= 0 ,0
Exp/Cntr(USF)=0,0
Exp/Cntr=0.3,0.1

Type RM Length L Ch R = 1 ,771     ,135.1,135.5,134.9
XS GIS Cut Line= 2
2157343.94466068680050.810677028 2157588.4985331680190.555746984
#Sta/Elev= 30
       0 1535.65    14.1 1530.34      40 1519.15    48.8 1515.83    61.2 1509.84
    78.1 1502.83    83.2 1501.01    93.5 1498.45      97 1497.33   113.3 1491.75
   119.2 1489.49   123.3 1487.07   129.3 1482.53   130.9 1481.74   133.8 1480.85
   138.5 1480.68   142.6 1480.18   147.11478.954   151.4 1478.38     158 1478.95
   163.1 1480.71     166 1481.21   175.3 1481.28   189.5 1480.27   193.8 1480.29
   198.3 1480.69   204.2 1481.61   216.8 1482.86   239.4 1485.77   281.7 1492.66
#Mann= 4 ,-1,0
       0      .1       0   147.1    .045       0     158      .1       0
     260     .06       0
Bank Sta=147.1,158
XS Rating Curve= 0 ,0
Exp/Cntr(USF)=0,0
Exp/Cntr=0.3,0.1

Type RM Length L Ch R = 1 ,636     ,150.6,148.1,146.6
XS GIS Cut Line= 3
 2157344.6041447680188.5194311692157483.90344588680263.973219309
 2157525.1773129680272.356973546
#Sta/Elev= 30
       0  1502.6     3.1 1501.14       9 1498.71    13.2 1497.16    17.7 1495.11
    22.3 1492.69    26.8 1490.59    35.9 1487.54    40.5  1485.3      45 1482.87
    49.6 1481.38    63.2 1480.95    73.9 1481.19    94.6 1481.13    97.5 1480.66
    99.6 1480.09   103.4 1478.51   104.1 1478.28   108.7 1477.97   110.6 1478.09
   112.91478.487   117.8  1479.3   121.2 1480.03   126.9 1481.63   131.4 1482.62
   144.2 1484.63   149.6 1485.21   158.4 1485.81   162.8 1486.27   200.5 1490.77
#Mann= 4 ,-1,0
       0      .1       0   103.4    .045       0   112.9      .1       0
  198.42     .06       0
Bank Sta=103.4,112.9
XS Rating Curve= 0 ,0
Exp/Cntr(USF)=0,0
Exp/Cntr=0.3,0.1

Type RM Length L Ch R = 1 ,488     ,128.7,135.4,138.9
XS GIS Cut Line= 4
2157211.88978021680234.3623254722157257.00653299680293.633353636
2157387.93358028680344.9426018982157461.35888382680353.789024012
#Sta/Elev= 30
       0 1531.67     3.5 1531.31     7.1 1530.38    13.6 1527.45    28.7 1522.25
    38.7 1517.76    50.7 1511.81    74.5 1501.04    86.5 1497.58      95  1494.1
   103.7 1492.05     108 1490.79   122.9 1485.09   129.4 1482.28   133.7 1481.07
     138 1480.43   142.3 1478.81   146.6 1477.54   150.9 1476.96   155.2  1476.8
   158.6 1477.54   163.8 1479.53   168.1 1480.25   176.7 1480.06   185.3 1480.34
   190.8 1480.75   215.1 1483.31   227.4 1484.25   267.7 1485.84   289.1 1487.25
#Mann= 3 ,-1,0
       0      .1       0   146.6    .045       0   158.6      .1       0
Bank Sta=146.6,158.6
XS Rating Curve= 0 ,0
Exp/Cntr(USF)=0,0
Exp/Cntr=0.3,0.1

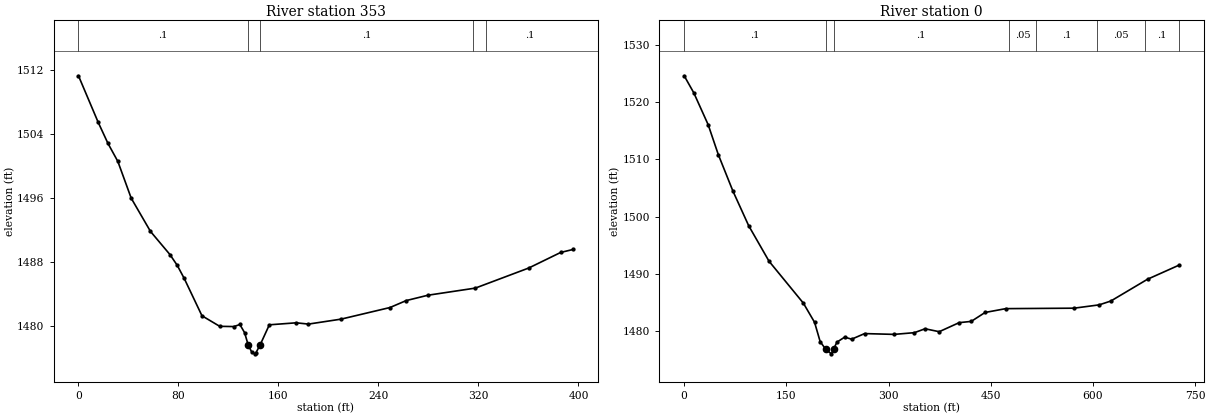
Type RM Length L Ch R = 1 ,353     ,336.7,352.4,336.7
XS GIS Cut Line= 4
2157172.98058472680321.1057951282157256.06995273 680419.65574903
2157274.20451558680439.4238493582157495.12892849680345.240323507
#Sta/Elev= 30
       0 1511.32    15.8 1505.49    23.6 1502.86    31.5 1500.61    42.2 1496.01
    57.6 1491.86    73.2 1488.96      79 1487.62    84.6 1485.98    98.8 1481.31
     113 1479.99   124.4 1479.96   129.1 1480.22   132.9  1479.2   135.7  1477.7
   138.5  1476.8   140.9 1476.55   141.8 1476.63  145.31 1477.66   152.7 1480.18
   174.2 1480.43     184 1480.27   210.1 1480.89   249.2 1482.34   262.2 1483.21
   279.6 1483.88   317.5 1484.77   360.2 1487.28   385.8 1489.23   395.9 1489.61
#Mann= 5 ,-1,0
       0      .1       0   135.7    .045       0  145.31      .1       0
  315.73     .05       0  325.73      .1       0
Bank Sta=135.7,145.31
XS Rating Curve= 0 ,0
Exp/Cntr(USF)=0,0
Exp/Cntr=0.3,0.1

Type RM Length L Ch R = 1 ,0       ,264,261.1,254.2
XS GIS Cut Line= 4
2157215.05031431680857.0634840752157122.29194085680711.187067691
2157134.97684662680658.8618313792157517.90243963680337.775154012
#Sta/Elev= 30
       0  1524.6    14.1 1521.62    35.2 1516.05    50.1 1510.82    71.5 1504.46
    94.7 1498.39   124.6 1492.18   174.9 1484.87   191.4 1481.51   199.6 1478.14
   207.9 1476.78   216.1    1476   219.2 1476.82   224.3 1478.05   235.6 1478.92
   245.8 1478.56   264.8 1479.54   308.3  1479.4   337.9  1479.7   353.6 1480.38
   374.4 1479.87   403.6 1481.45   421.4 1481.67   441.7 1483.23   472.1  1483.9
   572.3 1483.98   609.2 1484.56   626.3 1485.23   680.2 1489.04   726.4  1491.5
#Mann= 8 ,-1,0
       0      .1       0   207.9    .045       0   219.2      .1       0
  476.71     .05       0  516.71      .1       0  606.71     .05       0
  676.71      .1       0  726.44     .05       0
Bank Sta=207.9,219.2
XS Rating Curve= 0 ,0
Exp/Cntr=0.3,0.1
LCMann Table=0

Chan Stop Cuts=-1
Use User Specified Reach Order=0
Composite Channel Slope=5